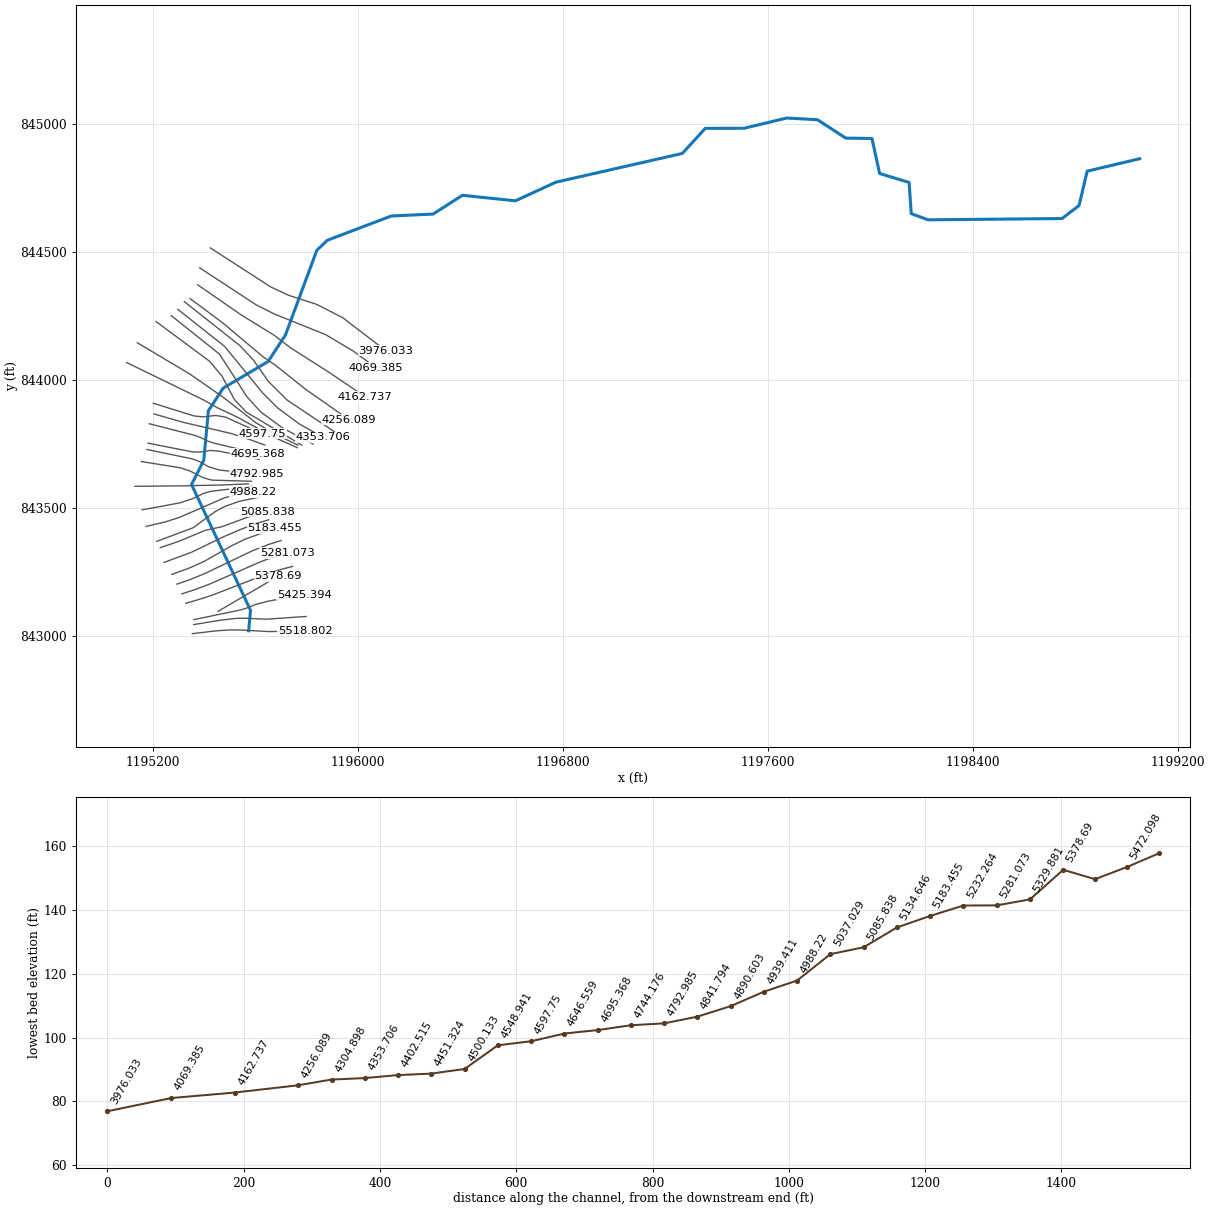
--- 242_ras.prj (project) ---

Proj Title=242
Current Plan=p01
Default Exp/Contr=0.3,0.1
English Units
Geom File=g01
Flow File=f01
Plan File=p01
Y Axis Title=Elevation
X Axis Title(PF)=Main Channel Distance
X Axis Title(XS)=Station
BEGIN DESCRIPTION:
RFD model 242 exported to HEC-RAS
END DESCRIPTION:

--- 242_ras.p01 (plan) ---

Plan Title=Plan 01
Program Version=4.10
Short Identifier=Plan 01
Geom File=g01
Flow File=f01
Subcritical Flow
Calc Critical at every XS
Secant Critical Depth

--- 242_ras.f01 (steady flow) ---

Flow Title=Flow 01
Program Version=5.01
Number of Profiles= 5
Profile Names=10yr,25yr,50yr,100yr,500yr
River Rch & RM=242,53,5518.802
  175.01  313.64  449.42  614.05 1112.08
River Rch & RM=242,53,4646.559
   178.7  320.41  459.32  627.87 1138.55
River Rch & RM=242,53,4548.941
  314.71  571.31  828.79 1147.54 2153.68
River Rch & RM=242,53,4451.324
  321.97  584.79  848.75 1175.77 2209.73
River Rch & RM=242,53,4304.898
  331.64  602.75  875.36 1213.45 2284.65
River Rch & RM=242,53,4162.737
  334.06  607.24  882.02 1222.88 2303.41
River Rch & RM=242,53,4069.385
  337.68  613.97     892 1237.03 2331.58
River Rch & RM=242,53,3976.033
   340.7  619.58  900.32 1248.82 2355.08
River Rch & RM=242,53,3789.329
  344.32  626.32  910.31 1262.97  2383.3
River Rch & RM=242,53,3695.976
  371.46   676.8  985.25  1369.3 2595.88
River Rch & RM=242,53,3602.624
   382.3  696.98 1015.25 1411.91 2681.34
River Rch & RM=242,53, 3415.92
  393.13  717.16 1045.25 1454.56 2767.03
River Rch & RM=242,53,3322.568
  394.33  719.41 1048.59  1459.3 2776.57
River Rch & RM=242,53,3229.216
  407.55  744.07 1085.28  1511.5 2881.64
River Rch & RM=242,53,3135.864
  414.16  756.39 1103.64 1537.62 2934.31
River Rch & RM=242,53,2989.479
  418.96  765.36 1116.99 1556.62 2972.66
River Rch & RM=242,53, 2811.81
  428.56  783.28 1143.69 1594.66 3049.49
River Rch & RM=242,53,2525.197
  447.14  818.01 1195.46 1668.44 3198.82
River Rch & RM=242,53,2320.343
  450.13  823.61 1203.81 1680.35 3222.96
River Rch & RM=242,53,2097.892
  527.21  967.98 1419.54 1988.58 3850.95
River Rch & RM=242,53, 1910.34
  625.32 1152.42 1696.08 2385.18 4667.11
River Rch & RM=242,53,1722.788
  646.66 1192.63  1756.5 2472.02  4846.9
River Rch & RM=242,53,1535.235
   651.4 1201.56 1769.93 2491.33 4886.94
River Rch & RM=242,53,1208.748
  661.47 1220.54 1798.47 2532.39  4972.1
River Rch & RM=242,53,964.9028
  671.53 1239.53 1827.02 2573.47 5057.39
River Rch & RM=242,53,715.5412
 1110.13  2071.8 3086.17 4396.84 8908.58
River Rch & RM=242,53,468.3921
 1121.79 2094.04 3119.99 4446.07 9014.06
River Rch & RM=242,53, 52.9598
 1133.45 2116.28 3153.81 4495.32 9119.64
Boundary for River Rch & Prof#=242,53,1
Up Type= 0
Dn Type= 2
Boundary for River Rch & Prof#=242,53,2
Up Type= 0
Dn Type= 2
Boundary for River Rch & Prof#=242,53,2
Up Type= 0
Dn Type= 2
Boundary for River Rch & Prof#=242,53,2
Up Type= 0
Dn Type= 2
Boundary for River Rch & Prof#=242,53,2
Up Type= 0
Dn Type= 2

--- 242_ras.g01 (geometry) ---

Geom Title=242
Program Version=4.10

River Reach=242,53
Reach XY= 30
1195572.55176052843021.2986395361195579.90301606843101.345643923
1195349.72030053843592.2570155111195397.37939337843687.027388528
1195415.45698488843880.4027762711195472.97657895843968.599481419
1195648.27438465844072.6825465261195716.20228618844176.217809066
1195838.54791513 844506.87241599 1195879.3812376844546.039069906
1196129.38116696 844641.039034591196292.71445253844648.539027646
1196406.88108781844721.8723360151196613.54769316844700.205669746
1196771.43499756 844772.928579451197265.21417391844885.205596223
1197354.64131033844983.2023517191197506.04743937844983.538893536
1197672.71405822845023.5388768761197792.71402282845016.872208714
1197902.71398839844945.2055599991198005.21395826844943.538890854
1198035.21394551 844806.87226373 1198150.2139107844771.872270703
1198158.54723805844650.205639735 1198224.3805514844626.038978264
1198746.88039812844631.0389616641198813.54704666844681.872278064
1198845.21370792844816.0389041751199049.73254815844864.511556372

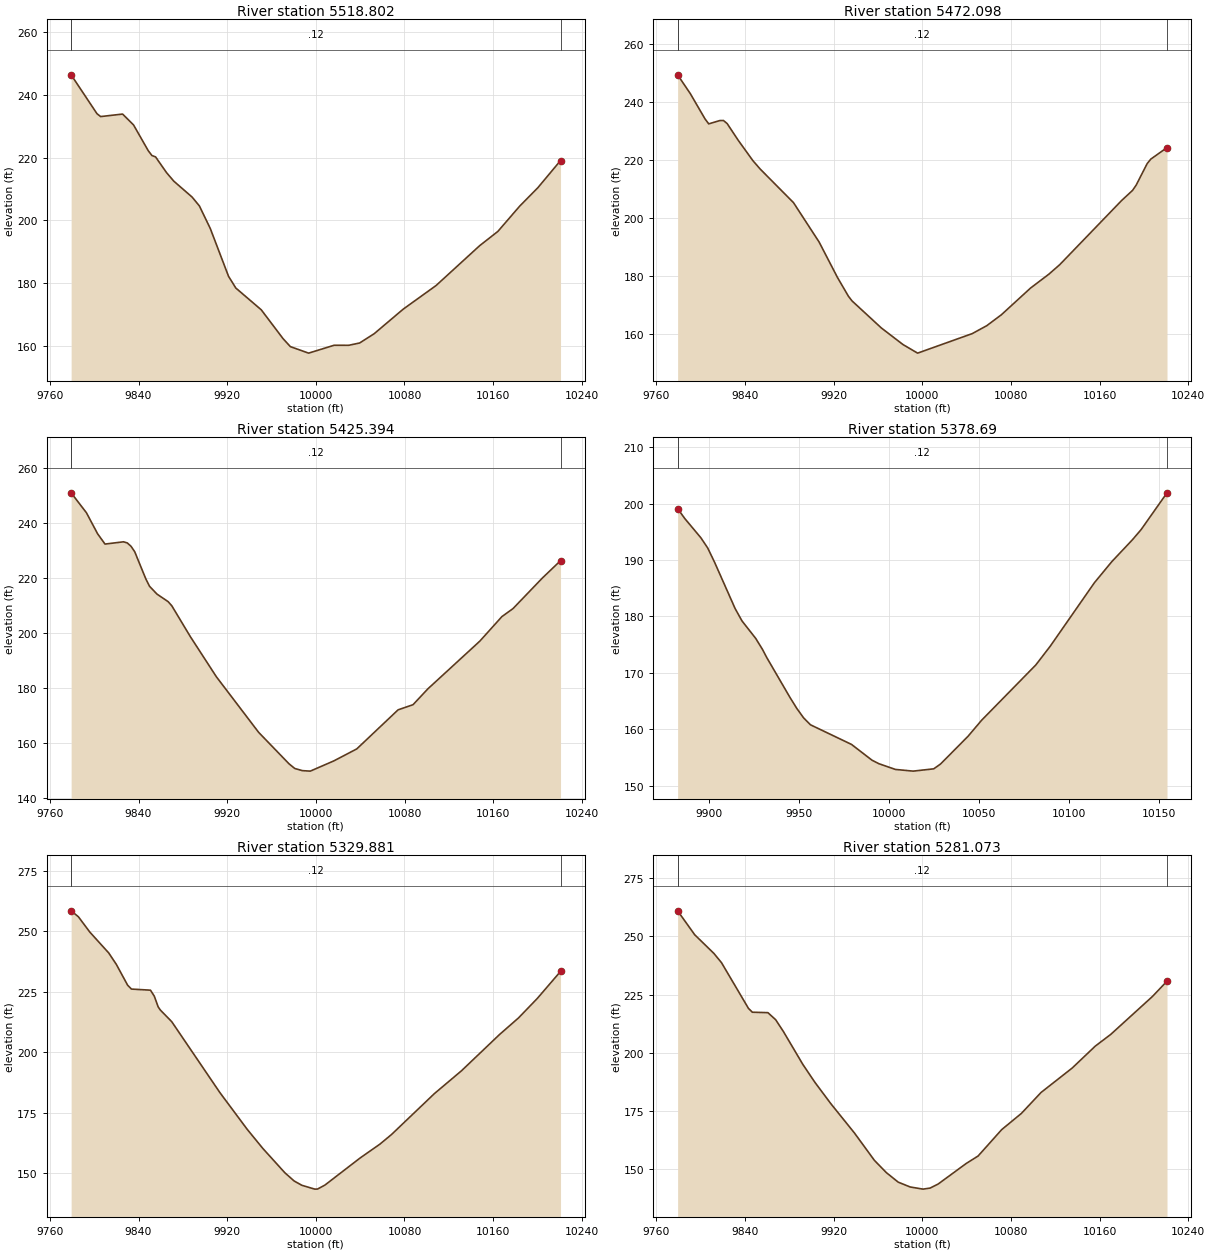
Type RM Length L Ch R = 1 ,5518.802,46.703900,46.703900,46.703900
XS GIS Cut Line= 6
1195352.70455707843009.9662606731195444.67087048 843021.08286276
1195499.93547795843024.7259298391195541.27246681843024.455051084
1195652.17604846843018.1480094791195793.29040348843021.458945238
#Sta/Elev= 30
9779.196246.36979802.509233.99269805.814233.07139825.642233.87189835.556230.3856
9848.775222.2082 9852.08220.66669855.385220.22859865.299215.20729871.908212.4753
9888.348207.43339894.924204.61459904.787197.39559921.227182.19289927.802178.4566
9950.768171.51539970.458162.32189977.035159.79069993.477157.723210016.51160.2303
10029.67160.216110039.53160.952310052.66 163.90810078.92171.751910108.46179.2424
10147.84191.951510164.25196.487110183.94204.540610200.34210.412910220.81219.0612
#Mann= 3 , 0 , 0
9779.196    0.12       09779.196    0.12       010220.81    0.12       0
#XS Ineff= 2 , 0
       0                               0
Bank Sta=9779.196,10220.81
Exp/Cntr=0.3,0.1

Type RM Length L Ch R = 1 ,5472.098,46.703800,46.703800,46.703800
XS GIS Cut Line= 6
1195357.99168497843045.4532566031195460.80304537843062.419501554
1195522.05596954843069.6003183841195553.09709704843070.413602321
1195642.49960876843066.6514033041195797.27904463843077.313376187
#Sta/Elev= 30
9779.202249.4549 9790.65242.97189803.951234.23839807.276232.53729817.252233.6742
9820.577233.69899823.902232.63929833.878226.88029847.179219.82249853.829216.9001
9883.754 205.3649906.877191.77119923.393179.58329933.303173.08129936.606171.4454
9962.917162.16059982.621 156.3829995.773153.438610045.07160.1722 10058.2162.9136
10071.33166.668710097.64175.876910114.08180.640210123.95183.934410179.86206.0978
10189.72209.586610193.01211.424110202.88218.814110206.17220.373610220.81224.3426
#Mann= 3 , 0 , 0
9779.202    0.12       09779.202    0.12       010220.81    0.12       0
#XS Ineff= 2 , 0
       0                               0
Bank Sta=9779.202,10220.81
Exp/Cntr=0.3,0.1

Type RM Length L Ch R = 1 ,5425.394,46.703900,46.703900,46.703900
XS GIS Cut Line= 6
1195359.04572697843065.0257958181195538.23832938843102.066926667
1195561.21746159843108.7055628511195600.75383665843124.379898926
1195650.14591174843137.2395249661195788.93462033843162.640820004
#Sta/Elev= 30
9779.192250.8496    9793 243.603 9803.05235.97489809.751232.21549826.502233.0417
9829.852232.62959833.202231.42759836.552229.44239846.603219.53299849.953216.8591
9856.654 214.0229866.704 211.2839870.054209.75589886.805198.52679910.257183.9571
9948.397163.74629975.767152.32239980.967150.61519987.867149.82579994.975149.6521
10016.15153.356210036.93157.729810074.22171.942410087.68173.804910101.07179.5672
10147.93196.907110167.91205.851710177.88208.742910204.47219.895910220.79226.1794
#Mann= 3 , 0 , 0
9779.192    0.12       09779.192    0.12       010220.79    0.12       0
#XS Ineff= 2 , 0
       0                               0
Bank Sta=9779.192,10220.79
Exp/Cntr=0.3,0.1

Type RM Length L Ch R = 1 , 5378.69,48.808700,48.808700,48.808700
XS GIS Cut Line= 2
1195453.29806015843097.2616130711195687.72143012843234.485049143
#Sta/Elev= 30
9882.706199.10479886.698197.33489895.606193.93379899.408 192.122 9903.21 189.603
9914.614181.39819918.416179.21029926.019176.11739929.821174.15279932.159172.7243
9945.027165.66859948.829163.7146 9952.63162.02749956.432160.79889979.241157.3166
9990.608154.52359994.448153.9008 10003.6152.887210013.46152.588310024.86152.9946
10028.66153.855310043.87158.752210051.47161.613710081.53171.402610089.49174.7054
   10114185.9504 10123.7189.704510135.11193.566810139.98 195.38610154.34201.8942
#Mann= 3 , 0 , 0
9882.706    0.12       09882.706    0.12       010154.34    0.12       0
#XS Ineff= 2 , 0
       0                               0
Bank Sta=9882.706,10154.34
Exp/Cntr=0.3,0.1

Type RM Length L Ch R = 1 ,5329.881,48.808800,48.808800,48.808800
XS GIS Cut Line= 6
1195326.89351498843128.5758131811195390.27328833843147.116026943
1195436.37495038843162.7236305861195644.00171533843243.330326828
1195695.08726699843259.7431265771195743.90498253843272.813249013
#Sta/Elev= 30
9779.183258.48969785.752256.02589796.007249.71469813.098241.06369819.935236.3461
 9830.19227.70059833.608226.10669850.773225.65039854.236223.1683  9857.7218.7563
9859.737217.40239869.968212.60649913.444183.24429938.099168.03989952.187 160.129
9972.015150.09469980.364146.69419987.409 144.8889999.073143.3069 10001.5143.3357
10008.17144.973510040.18 156.27410057.77161.905310068.32165.9247   10107182.8461
10131.32192.245210165.78207.300810182.83214.146210199.81222.208810220.81233.4123
#Mann= 3 , 0 , 0
9779.183    0.12       09779.183    0.12       010220.81    0.12       0
#XS Ineff= 2 , 0
       0                               0
Bank Sta=9779.183,10220.81
Exp/Cntr=0.3,0.1

Type RM Length L Ch R = 1 ,5281.073,48.808700,48.808700,48.808700
XS GIS Cut Line= 6
1195311.92418553843165.4886493011195361.43139218843181.503176937
1195420.09687603843203.6404801161195624.10549375843292.856912836
1195674.65594945843310.8491609061195723.09756835843325.246895931
#Sta/Elev= 30
9779.194260.96519794.656250.67519811.897242.69239818.794238.7042 9843.13219.0604
9846.636217.41759860.663217.23389867.676214.19859874.689209.09779892.223 194.989
9902.946187.40369917.298178.23559938.824165.50899956.763153.80189967.526148.5414
 9978.29144.42439989.053142.362510000.69  141.4410007.07141.903310014.28143.6234
10039.53152.430310050.34155.660710071.64167.002110089.39173.954610107.14182.9514
10135.18193.417110156.08202.861310170.01207.883510207.66224.178710220.81230.7597
#Mann= 3 , 0 , 0
9779.194    0.12       09779.194    0.12       010220.81    0.12       0
#XS Ineff= 2 , 0
       0                               0
Bank Sta=9779.194,10220.81
Exp/Cntr=0.3,0.1

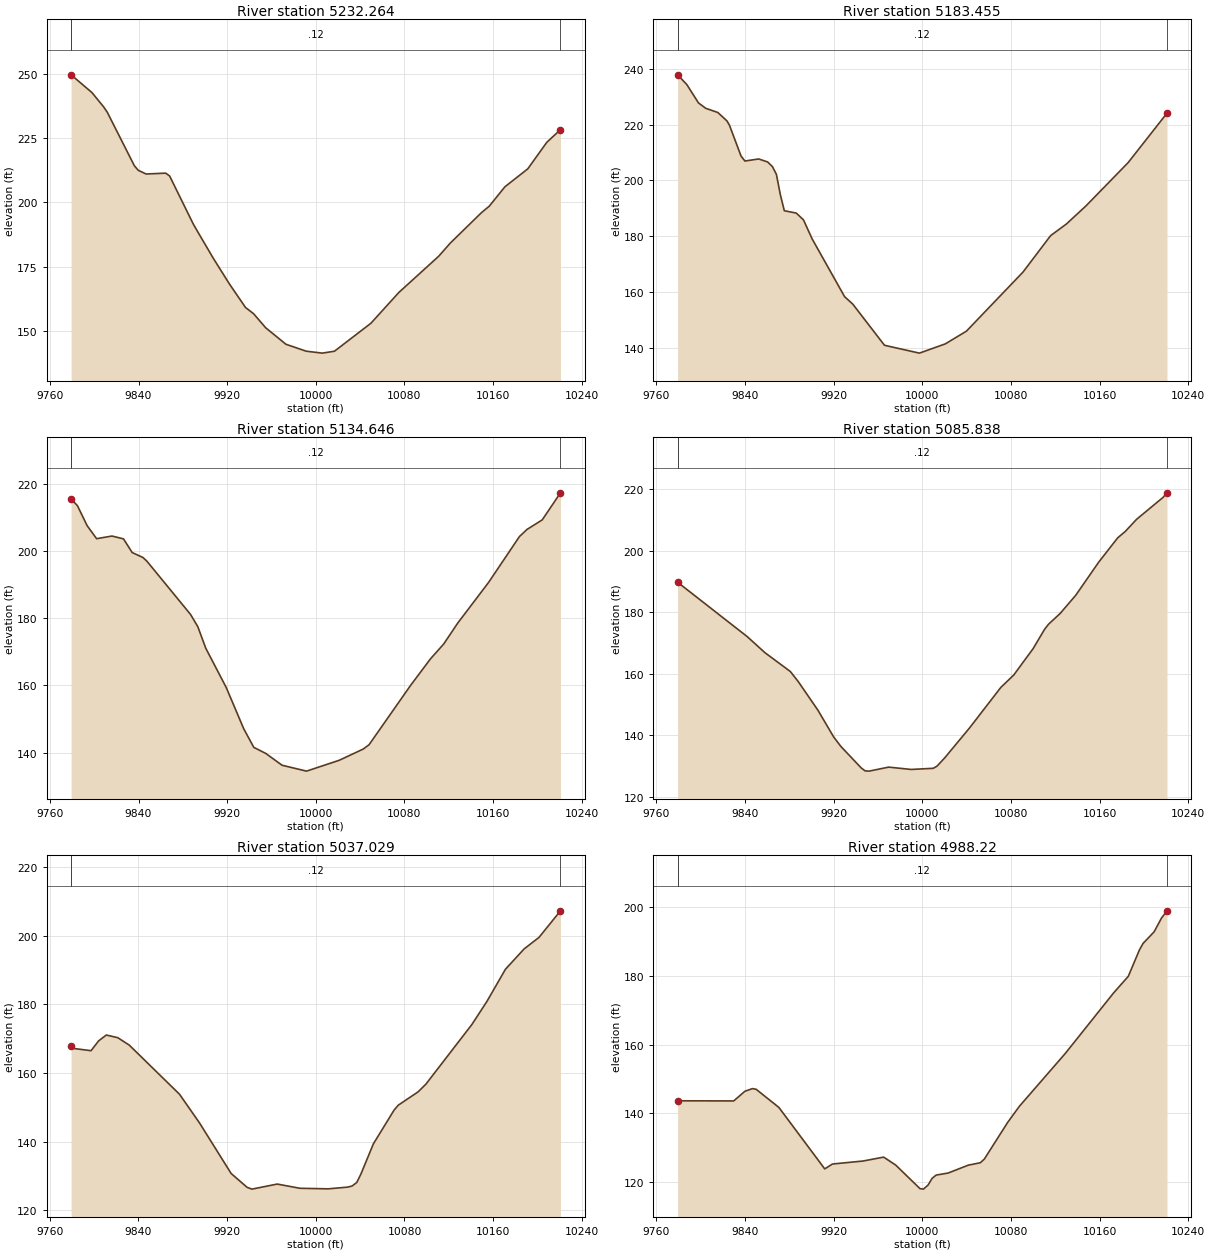
Type RM Length L Ch R = 1 ,5232.264,48.808800,48.808800,48.808800
XS GIS Cut Line= 6
1195292.51377649843203.4284255671195342.81986034 843220.82521849
1195399.97305634843244.1327438591195591.19270734843335.545839773
1195651.07211522843358.5949310031195699.29405182843373.708282257
#Sta/Elev= 30
9779.194249.54869797.942242.67019808.357237.19049811.828235.00159836.205214.2525
9839.748212.44979846.835211.0027 9864.55211.33949868.093210.22689889.352191.6235
9892.828189.0078 9907.44178.2907 9922.02168.2886  9936.6159.1154 9943.89156.6957
9954.825151.2254 9973.05144.83579991.275142.148710005.88141.388310016.85142.1302
10049.75153.002310075.02164.9958 10110.9179.035710121.45184.188810149.57196.0082
 10156.6198.520110170.66206.029510191.29213.001110208.48223.319810220.81228.2397
#Mann= 3 , 0 , 0
9779.194    0.12       09779.194    0.12       010220.81    0.12       0
#XS Ineff= 2 , 0
       0                               0
Bank Sta=9779.194,10220.81
Exp/Cntr=0.3,0.1

Type RM Length L Ch R = 1 ,5183.455,48.808700,48.808700,48.808700
XS GIS Cut Line= 6
1195272.86092993843241.5237190371195340.58579635843266.164279838
1195397.57333397843291.4611022271195505.35335607843353.058347497
1195558.12034357843378.7765206951195674.95384339843420.808414805
#Sta/Elev= 30
9779.213237.84379787.559234.32939798.033227.77869804.579225.84959815.489224.3503
 9823.77221.31739825.963 219.8219836.437208.74829839.928206.96199852.357207.6984
9860.443206.62249864.735204.97229868.325202.21059871.914194.87399875.504189.1502
9886.272188.31129892.789185.86739900.631179.03099929.862158.37479937.277  155.69
9965.886140.94449997.395138.133210020.74141.441410039.75145.979110090.85 167.165
10115.79180.237310129.94184.367310147.63190.857610185.73206.385310220.77224.0944
#Mann= 3 , 0 , 0
9779.213    0.12       09779.213    0.12       010220.77    0.12       0
#XS Ineff= 2 , 0
       0                               0
Bank Sta=9779.213,10220.77
Exp/Cntr=0.3,0.1

Type RM Length L Ch R = 1 ,5134.646,48.808700,48.808700,48.808700
XS GIS Cut Line= 6
 1195242.5162406843288.1822975781195350.75368494843328.564368438
1195471.26393629 843386.910745041195542.39505737843417.504346326
1195602.42894433843440.1532244341195650.77206957  843454.8694674
#Sta/Elev= 30
 9779.19215.39649784.873 213.442 9793.68207.4691  9802.2 203.6249816.061204.4118
9826.457203.56979834.282199.5115    9844198.03169847.537196.95339886.974181.1007
9893.517177.46649900.713171.05799919.213159.35079934.922147.13949944.045141.5841
9954.878139.78049969.539136.27449991.651134.522310021.03137.730910042.67141.0622
10048.02142.350210085.52159.998410103.38167.859710115.44172.318110127.98178.4866
10156.03190.669410183.78 204.26310190.64206.383410204.35209.2197 10220.8217.2588
#Mann= 3 , 0 , 0
 9779.19    0.12       0 9779.19    0.12       0 10220.8    0.12       0
#XS Ineff= 2 , 0
       0                               0
Bank Sta=9779.19,10220.8
Exp/Cntr=0.3,0.1

Type RM Length L Ch R = 1 ,5085.838,48.808800,48.808800,48.808800
XS GIS Cut Line= 6
1195227.68158331 843346.017714931195297.44763127843369.668948369
1195404.29430577843413.9940995661195468.64587697843427.786673744
1195568.37941556843464.852688637 1195645.1489172843486.948711182
#Sta/Elev= 30
9779.224189.7114 9842.14171.99989857.897166.84649880.939 160.6939888.043157.4319
9905.802 148.125 9920.01139.43549926.393136.38949944.874129.34729948.426128.3857
9951.978128.3038 9969.69129.60899990.009128.845610009.92129.223610013.24129.9075
10019.97132.499210042.68142.358210070.93 155.54510082.49159.530510099.99168.1118
10110.49174.491110113.99176.084410124.49 179.59610138.49185.483210159.15196.2195
10176.34204.149110183.21 206.23610193.43210.187210217.13217.256510220.79218.7805
#Mann= 3 , 0 , 0
9779.224    0.12       09779.224    0.12       010220.79    0.12       0
#XS Ineff= 2 , 0
       0                               0
Bank Sta=9779.224,10220.79
Exp/Cntr=0.3,0.1

Type RM Length L Ch R = 1 ,5037.029,48.808700,48.808700,48.808700
XS GIS Cut Line= 6
1195214.38301952843370.6447728411195356.09043676843423.653194005
1195442.10877681843486.8131040361195479.15659873843506.772142829
1195536.61785812843526.8913223891195614.78215575843543.350967661
#Sta/Elev= 30
 9779.26167.9732 9782.35167.08669797.225166.47769804.115169.34619811.005 171.035
 9821.34170.26229831.675168.10629877.018153.8045 9894.97145.49539923.603130.7204
9938.037126.68229942.281 126.1659965.157127.6385 9985.67126.414610011.19 126.248
10028.51126.741610032.74127.070610036.97128.116610040.79130.633810051.97139.3698
10070.61149.175810074.33150.591410092.28154.491610099.34156.7407 10140.8 174.099
10154.28180.779510171.13190.212210187.98196.1266 10201.3199.448110220.71207.1991
#Mann= 3 , 0 , 0
 9779.26    0.12       0 9779.26    0.12       010220.71    0.12       0
#XS Ineff= 2 , 0
       0                               0
Bank Sta=9779.26,10220.71
Exp/Cntr=0.3,0.1

Type RM Length L Ch R = 1 , 4988.22,48.808800,48.808800,48.808800
XS GIS Cut Line= 6
1195172.42242658843428.7277377081195248.16828773843446.664404901
1195304.55064214 843464.94476785 1195478.4002609843540.662532791
 1195525.6569816  843552.70258571195590.71217073843563.311073076
#Sta/Elev= 30
9779.221 143.6269829.809143.58739839.924146.40379846.667147.17779850.039146.9938
9870.571141.70189911.959123.78969918.933125.21029946.646126.08229965.118127.2221
9976.037124.88899997.933118.0312   10001117.891710005.23119.088210008.85121.0309
10012.48121.978410023.35122.582110041.48124.872310052.36125.580410055.98126.6495
10077.15137.391110087.66142.051410128.91157.3843 10172.6 175.05410185.89179.9073
10195.87187.556510199.19189.478310209.16192.859810215.81196.857410220.76198.9812
#Mann= 3 , 0 , 0
9779.221    0.12       09779.221    0.12       010220.76    0.12       0
#XS Ineff= 2 , 0
       0                               0
Bank Sta=9779.221,10220.76
Exp/Cntr=0.3,0.1

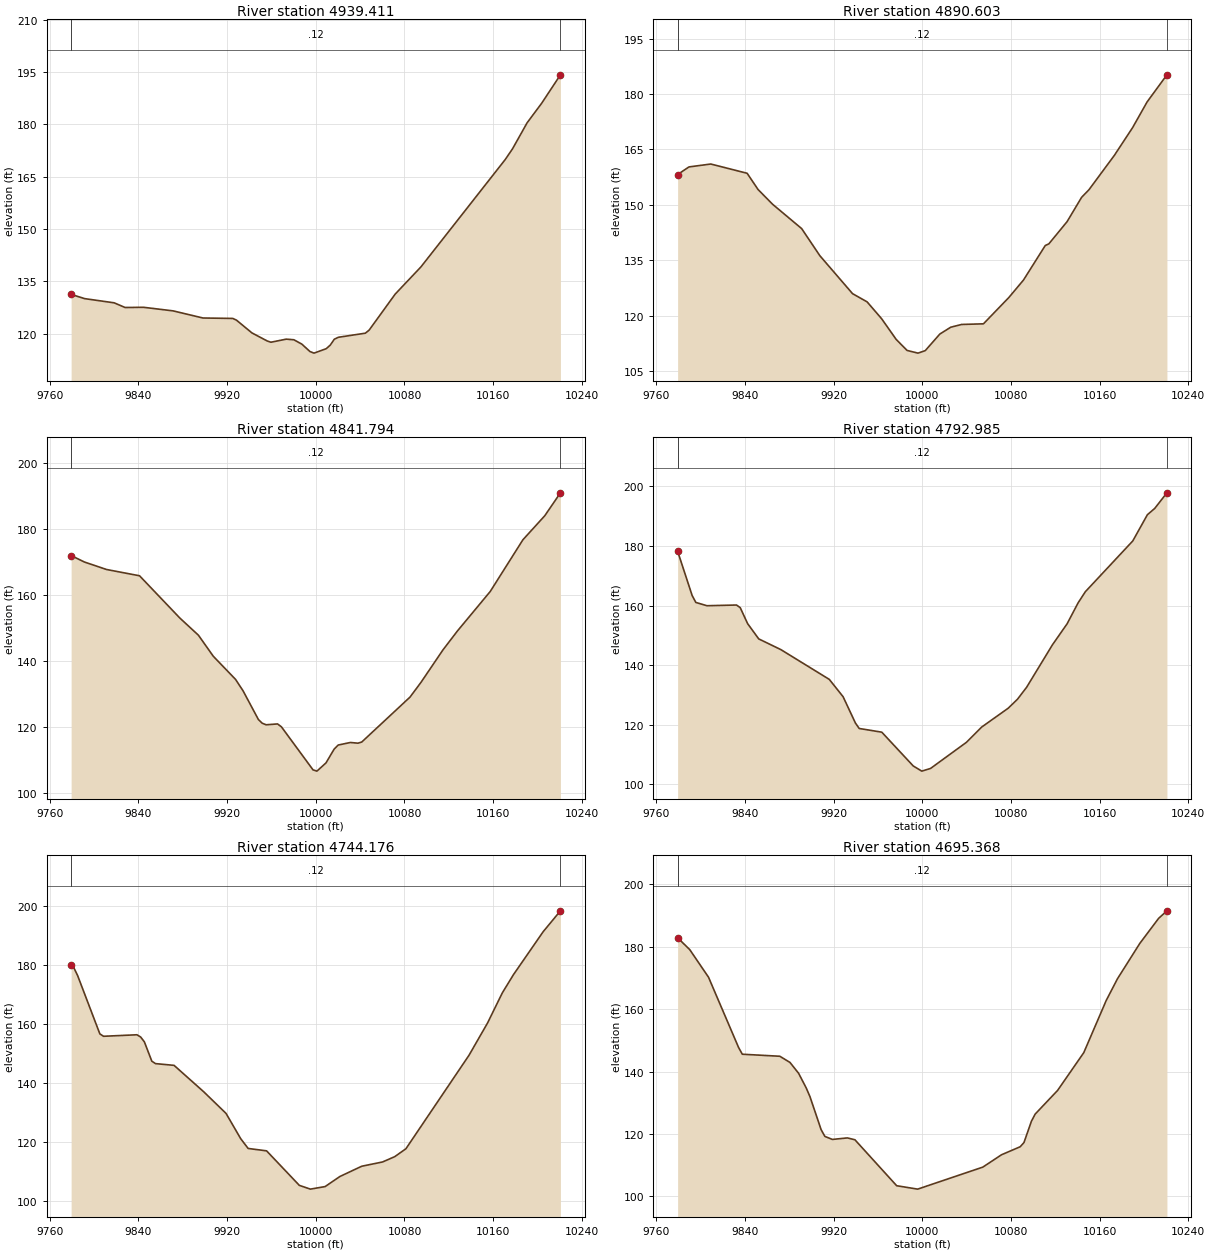
Type RM Length L Ch R = 1 ,4939.411,48.808700,48.808700,48.808700
XS GIS Cut Line= 6
1195157.06714615843493.5430499081195302.28542273843520.479339231
1195354.45058478843537.2945468431195396.39265458 843557.86320084
1195426.85819213843566.2122447541195586.22991347 843585.01940704
#Sta/Elev= 30
9779.256131.22289791.484130.00179818.033128.80539827.989127.45639844.582127.5191
9871.278126.4916 9898.19 124.4519925.102124.32489928.501123.8197 9942.29120.1941
9956.078117.87759959.525117.50379973.313118.38439980.207118.21249987.414116.9594
9994.718 114.841 9998.37114.380710009.43 115.65810013.07116.689610016.71118.3711
10020.35118.9231 10044.7120.0961 10048.1120.971510071.63131.300610094.86139.1038
10170.88169.866210177.47 172.94310190.65180.407410203.83186.035410220.71194.1594
#Mann= 3 , 0 , 0
9779.256    0.12       09779.256    0.12       010220.71    0.12       0
#XS Ineff= 2 , 0
       0                               0
Bank Sta=9779.256,10220.71
Exp/Cntr=0.3,0.1

Type RM Length L Ch R = 1 ,4890.603,48.808800,48.808800,48.808800
XS GIS Cut Line= 6
1195129.37865185843585.4723594061195337.70209414843587.532679342
1195349.17614702843588.0990108811195351.16391449843588.319873875
1195466.76041453  843590.41467261195570.85741764843595.113588134
#Sta/Elev= 30
9779.178158.20249789.429160.25889809.115161.04519841.925158.53939851.768154.1485
9864.892150.1546 9891.14143.56439907.545136.23279937.074125.95169950.198123.7308
9963.322119.16369976.446113.56999986.289110.58099996.142109.853710002.72110.5353
10015.84115.016610025.69116.866410035.53117.614710055.22117.786910078.19124.9277
10091.32129.6249   10111138.977710114.29139.4454 10130.7145.446110143.84152.0411
10150.41154.0681 10173.4163.398210189.82170.889910202.96177.867910220.82185.1911
#Mann= 3 , 0 , 0
9779.178    0.12       09779.178    0.12       010220.82    0.12       0
#XS Ineff= 2 , 0
       0                               0
Bank Sta=9779.178,10220.82
Exp/Cntr=0.3,0.1

Type RM Length L Ch R = 1 ,4841.794,48.808700,48.808700,48.808700
XS GIS Cut Line= 6
1195153.93415008843682.0592998521195305.00520425843658.001597364
1195344.51634831843644.7326327631195395.71952656843618.689073965
1195429.26516279843609.5873648851195583.56584168843605.125117607
#Sta/Elev= 30
9779.249171.89599791.302169.93649811.171167.67899840.974165.7726  9877.4152.9412
9894.121147.75029907.506141.38499927.583134.37259934.344 130.9179948.187 122.215
9951.648121.08919955.109120.61549965.492120.87159968.953119.99869997.477106.9539
   10001106.567610009.17109.057310016.52113.230110020.19114.474510031.21115.2472
10038.03115.040510041.43115.385410085.02129.014510094.91133.488410114.68143.2953
10127.81 149.06710157.33161.002110186.86176.696610206.55183.965410220.69 190.914
#Mann= 3 , 0 , 0
9779.249    0.12       09779.249    0.12       010220.69    0.12       0
#XS Ineff= 2 , 0
       0                               0
Bank Sta=9779.249,10220.69
Exp/Cntr=0.3,0.1

Type RM Length L Ch R = 1 ,4792.985,48.808700,48.808700,48.808700
XS GIS Cut Line= 6
1195175.99288526843729.145439427 1195351.7057417843692.727433004
1195377.51757783 843683.598037411195414.42381657843662.587225308
1195456.45040257843649.3329933361195603.40003049 843632.77607914
#Sta/Elev= 30
9779.239178.26559792.315 163.4359795.654161.07499805.671159.97079832.383160.2044
9835.721159.32869842.399153.96779852.416148.8423 9872.45145.23049916.115135.2434
9928.524129.44629939.713120.57289943.084 118.7749963.459117.53289991.839106.1904
 9999.56104.460710007.47105.364110039.82114.126210053.58119.248110077.49125.5676
10085.93128.603710094.12132.5964 10117.4146.831510130.67153.909610140.55 160.909
10147.13164.674910189.92 181.71410203.09190.503910209.67192.609510220.73197.8607
#Mann= 3 , 0 , 0
9779.239    0.12       09779.239    0.12       010220.73    0.12       0
#XS Ineff= 2 , 0
       0                               0
Bank Sta=9779.239,10220.73
Exp/Cntr=0.3,0.1

Type RM Length L Ch R = 1 ,4744.176,48.808800,48.808800,48.808800
XS GIS Cut Line= 6
 1195179.8549987 843753.949377111195352.50027731843720.050875105
1195380.67377614843719.0529491981195422.88547844843725.524207149
1195456.90573047843722.7724378081195614.19190103843690.916187854
#Sta/Elev= 30
9779.241180.06749781.716179.02529785.064176.43059805.154 156.5929808.502155.7736
9838.637156.28589841.985155.51439845.333153.8786 9852.03 147.3269855.378146.4909
 9872.12145.90029898.906136.91339918.996129.58749932.304120.96289938.957117.6776
9955.584116.86859985.153  105.149995.134103.867610008.43104.739210021.68108.1443
10041.46111.645110060.24113.091110071.27114.908310081.31117.583710138.21149.3161
10154.95160.279710168.34170.552710178.38  176.7310205.16 191.29710220.72198.3777
#Mann= 3 , 0 , 0
9779.241    0.12       09779.241    0.12       010220.72    0.12       0
#XS Ineff= 2 , 0
       0                               0
Bank Sta=9779.241,10220.72
Exp/Cntr=0.3,0.1

Type RM Length L Ch R = 1 ,4695.368,48.808700,48.808700,48.808700
XS GIS Cut Line= 6
1195184.77225969 843829.794603461195360.87254447843784.740603017
 1195385.2535639843775.9777382281195411.58567723843762.324022476
1195431.62272426843755.5419556591195609.53833113843712.608878505
#Sta/Elev= 30
 9779.21 182.8959790.183179.08519807.115170.24589834.207147.75449837.594145.5777
9871.459144.92719880.626142.94219888.392139.47339895.165134.84079898.551132.0857
9908.711121.41739912.097119.2475 9918.87118.27889932.416118.76279939.189118.1742
9976.896103.44379995.845102.353810054.64 109.40510071.52113.364310088.39115.9348
10091.77117.271410098.52124.124510101.89126.4004 10122.1133.968410145.77146.0956
10166.02162.812110176.14169.750610196.39181.122310213.27189.101210220.79 191.525
#Mann= 3 , 0 , 0
 9779.21    0.12       0 9779.21    0.12       010220.79    0.12       0
#XS Ineff= 2 , 0
       0                               0
Bank Sta=9779.21,10220.79
Exp/Cntr=0.3,0.1

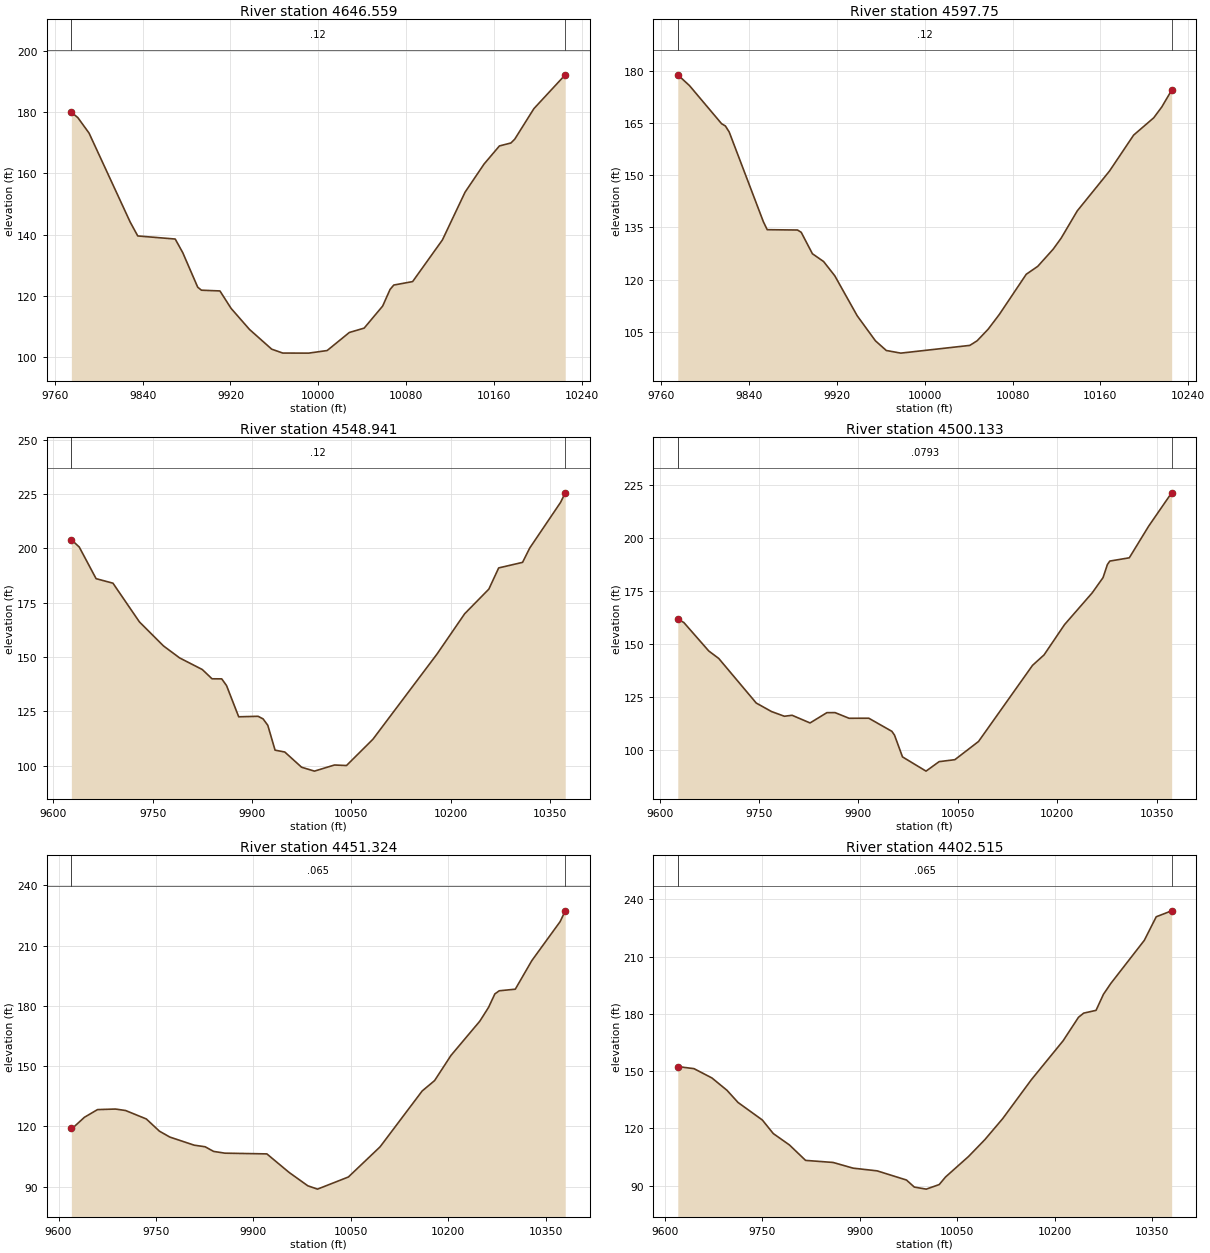
Type RM Length L Ch R = 1 ,4646.559,48.808800,48.808800,48.808800
XS GIS Cut Line= 6
1195202.88289804843868.1069535471195317.15007813843835.277411015
1195421.47243407843811.1598579371195505.93199939843791.099075766
1195556.53360812843775.3504528691195635.61478129843746.568846929
#Sta/Elev= 30
9775.036179.89159780.908 178.1759791.149173.11189828.698 144.0099835.525139.5259
9869.661 138.5199876.488134.09649890.142122.79939893.555 121.8139910.398121.5725
  9920.5115.90089937.337108.99759957.541102.56379967.643101.29419991.215 101.271
10008.06102.114110028.29108.015810041.78109.433610058.64116.645410065.39122.0741
10068.76123.497610085.93124.628710113.07138.226110133.68153.806910151.02163.0092
10164.99168.913710175.46169.877210178.96171.125610196.41181.095610224.96192.1311
#Mann= 3 , 0 , 0
9775.036    0.12       09775.036    0.12       010224.96    0.12       0
#XS Ineff= 2 , 0
       0                               0
Bank Sta=9775.036,10224.96
Exp/Cntr=0.3,0.1

Type RM Length L Ch R = 1 , 4597.75,48.808700,48.808700,48.808700
XS GIS Cut Line= 6
1195200.28259456843909.780280514 1195359.7559295843860.226731562
1195395.68006722843856.3919759561195442.98684991843862.275034588
1195482.45939956843855.6984585541195626.65797288843790.004798873
#Sta/Elev= 30
9775.171178.92059785.813175.82719815.055164.86169818.519164.20949821.983 162.483
9853.161136.61639856.626134.36759884.179134.27479887.576133.61079897.767127.4475
9907.958125.20619918.149121.09839938.531109.60939955.135102.40019965.03399.61554
9978.23198.8545510041.11 101.08110047.75102.405710057.83105.755710067.99109.9952
10092.48121.543810102.97123.828110116.98 128.75210124.31131.959510138.97 139.795
10168.28151.238310190.26 161.58210208.58166.563510215.91169.688210224.88174.4976
#Mann= 3 , 0 , 0
9775.171    0.12       09775.171    0.12       010224.88    0.12       0
#XS Ineff= 2 , 0
       0                               0
Bank Sta=9775.171,10224.88
Exp/Cntr=0.3,0.1

Type RM Length L Ch R = 1 ,4548.941,48.808800,48.808800,48.808800
XS GIS Cut Line= 6
1195096.09207313844068.8991517831195398.70286677843921.560860593
1195448.92009488843892.7508655071195525.28945281843857.083977044
1195672.36547134843776.919527214 1195762.6402543843736.164170466
#Sta/Elev= 30
9627.308203.95349639.195200.5977 9664.64186.04479690.086183.96679730.071166.1529
9766.422155.10889790.758149.60759824.967144.27259839.603140.0236 9854.24139.9912
9861.558136.87819879.854122.55639909.127122.78879916.711121.57889923.764118.6439
9934.741107.22139949.378106.3705 9974.7699.371429994.17897.5850510024.42100.4025
10042.53100.155810082.36112.221210179.21 151.43410220.88169.922410257.38181.2485
10272.19190.982510308.23193.536510319.03200.113310365.65221.133610372.64225.4989
#Mann= 3 , 0 , 0
9627.308    0.12       09627.308    0.12       010372.64    0.12       0
#XS Ineff= 2 , 0
       0                               0
Bank Sta=9627.308,10372.64
Exp/Cntr=0.3,0.1

Type RM Length L Ch R = 1 ,4500.133,48.808700,48.808700,48.808700
XS GIS Cut Line= 6
1195138.26143132844145.8202439921195342.81696739844024.066058244
1195471.08279743843934.6949534681195601.46132432843833.203582784
1195675.85977278843789.2698031591195764.98700981843746.079114902
#Sta/Elev= 30
9627.323161.7269 9636.43 160.1559674.113146.72989689.186143.2066 9745.71 122.233
9768.817118.21959788.194116.0045 9799.82116.46469826.948112.85169852.344 117.699
9864.672117.71839885.863115.04929915.579115.08129950.345108.92289954.375107.1333
9966.46596.8651110001.9890.1686910021.6894.6301610045.4595.5569310081.18104.1237
10162.62139.953610180.08144.895710210.91159.125510252.83 174.14510269.11181.2955
10275.61 187.40910279.29189.067410308.71190.612310337.99205.534510372.63221.2011
#Mann= 3 , 0 , 0
9627.323  0.0793       09627.323  0.0793       010372.63  0.0793       0
#XS Ineff= 2 , 0
       0                               0
Bank Sta=9627.323,10372.63
Exp/Cntr=0.3,0.1

Type RM Length L Ch R = 1 ,4451.324,48.808800,48.808800,48.808800
XS GIS Cut Line= 6
1195210.93241874844229.0625808161195419.59980662844074.057957664
1195468.15577879844016.4199497471195517.16972899 843923.98739017
1195563.76946254843874.8954857311195779.86947897843746.478092734
#Sta/Elev= 30
9619.712119.32349624.683120.02179639.793124.48849660.004128.32349687.621128.5974
9703.175127.87079735.143123.66329755.339117.57649771.496114.62879808.928110.6006
 9825.69109.81159838.757107.49739856.208106.62139920.785106.25939954.81297.08377
9983.80190.377759998.77588.7127510046.2994.7519310095.15109.788710159.95137.6072
 10179.1142.785310204.28155.301810248.75172.390310262.15179.233510271.88185.9525
10278.64187.506810303.34 188.297 10328.8  202.5310372.45221.981110380.25227.3285
#Mann= 3 , 0 , 0
9619.712   0.065       09619.712   0.065       010380.25   0.065       0
#XS Ineff= 2 , 0
       0                               0
Bank Sta=9619.712,10380.25
Exp/Cntr=0.3,0.1

Type RM Length L Ch R = 1 ,4402.515,48.808700,48.808700,48.808700
XS GIS Cut Line= 6
1195270.35829424844252.0666164091195458.64124638844101.790337783
1195565.97546125 843935.09550254 1195619.7031747843875.780516531
1195706.34797294843812.4280948641195823.65636863843750.729223373
#Sta/Elev= 30
9619.687152.43479644.713151.33059672.341146.45199695.562139.97019712.481133.6274
9749.947124.44339766.753117.35629791.661 111.3829816.524   103.39858.969102.2173
9889.60799.242789926.692 97.82199971.88593.017739983.96689.3220210002.3788.25388
10022.2890.6428110032.0694.6134610067.41105.329310092.54114.142210120.09125.1857
10164.18  145.5410213.07165.916110236.82178.248310244.74180.405910263.81181.8622
10275.17190.239710286.53195.930510338.21218.551510356.51230.868110380.27233.9778
#Mann= 3 , 0 , 0
9619.687   0.065       09619.687   0.065       010380.27   0.065       0
#XS Ineff= 2 , 0
       0                               0
Bank Sta=9619.687,10380.27
Exp/Cntr=0.3,0.1

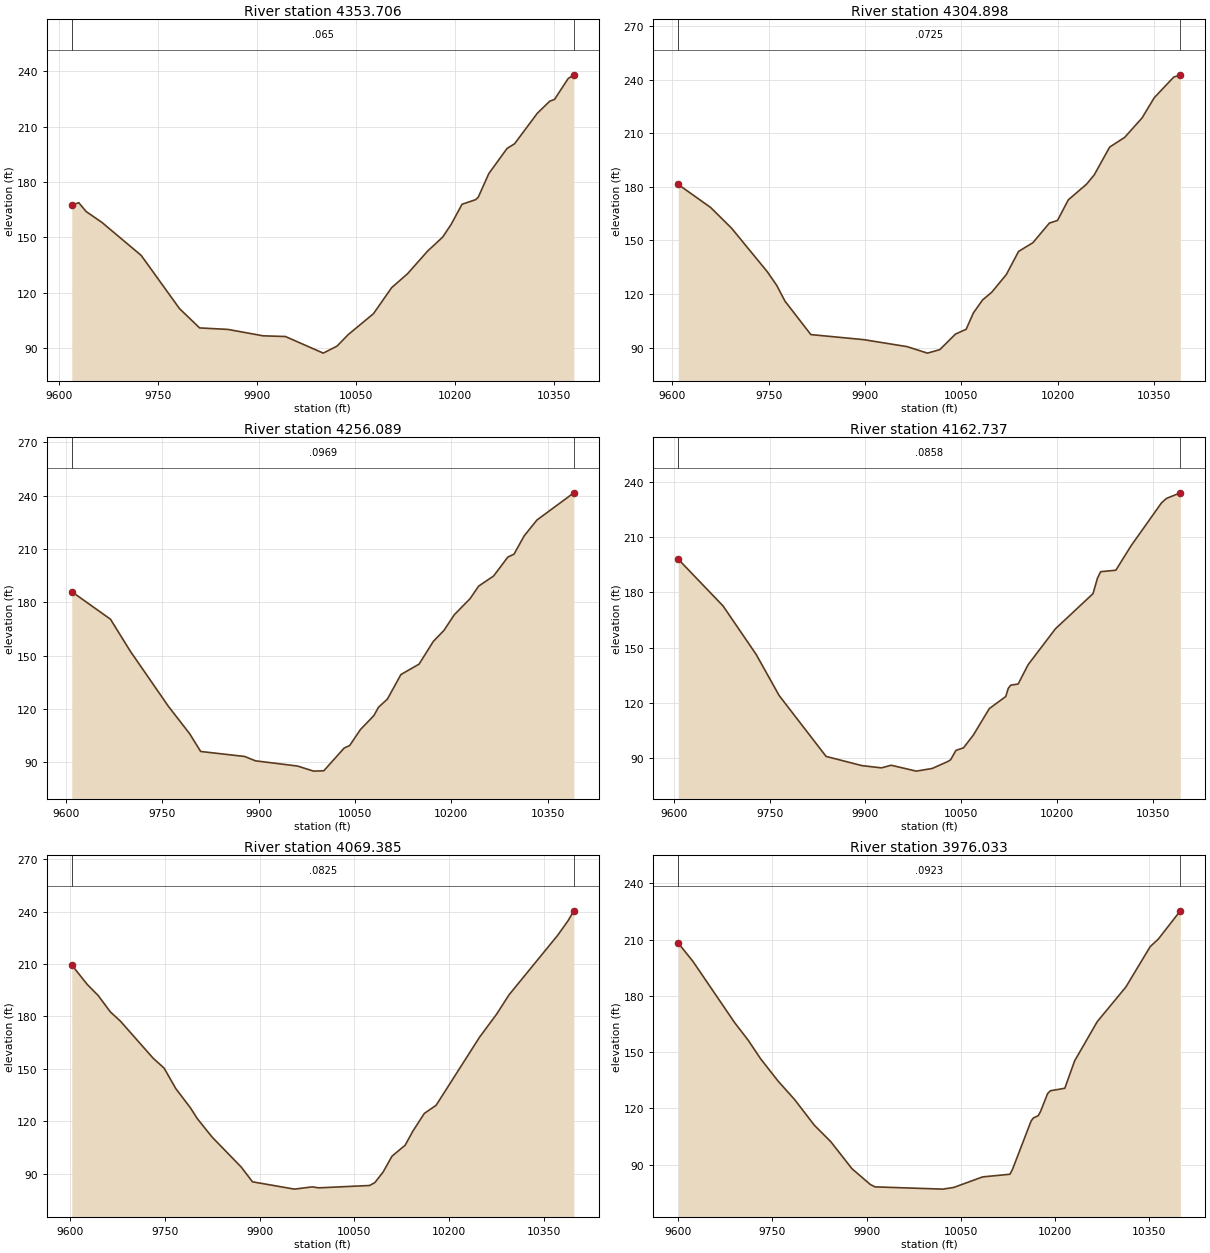
Type RM Length L Ch R = 1 ,4353.706,48.808700,48.808700,48.808700
XS GIS Cut Line= 6
1195296.00380607844276.6534816041195479.00203389844131.554369403
1195627.20084603843950.2250677671195685.23626032843891.803718162
1195768.16565509843830.2725196341195860.92973981843777.562581637
#Sta/Elev= 30
9619.688 167.4069630.224168.85089641.525164.01879665.373  158.15 9724.96 140.229
9782.908111.43339813.367 100.9719856.335100.15679909.57796.686349943.37296.31223
10000.6987.3106710021.56 91.118710038.5397.35979 10076.7108.649210104.25122.7714
10128.42 130.34410158.57142.523610181.58150.181410194.32156.995910210.92167.9741
10231.58170.482110235.55171.841310251.44184.555410279.03198.175310290.51200.7546
10324.93217.260210343.68223.785110351.12224.817510371.55236.032110380.32238.1132
#Mann= 3 , 0 , 0
9619.688   0.065       09619.688   0.065       010380.32   0.065       0
#XS Ineff= 2 , 0
       0                               0
Bank Sta=9619.688,10380.32
Exp/Cntr=0.3,0.1

Type RM Length L Ch R = 1 ,4304.898,48.808800,48.808800,48.808800
XS GIS Cut Line= 6
1195321.41510831844306.5686033411195537.43742292   844135.645395
1195590.14570126844079.5983776351195649.77081638843994.667585643
1195723.47476996843921.6969149881195906.47881101843799.202857572
#Sta/Elev= 30
 9609.48181.29059660.027168.35369692.632156.72689748.071132.40219762.754 124.749
9775.485 115.9869815.79397.228879897.98494.39893 9965.4390.490189997.10786.85027
10016.3688.7981510040.6797.4828810057.39100.227210068.55109.313710082.95116.6487
10097.17120.942410119.89130.867510138.86143.781310161.16148.682410186.86 159.671
10199.44161.131610216.23172.656510244.74181.479710256.78186.7626 10280.6202.2275
10303.89207.628210331.04218.569510349.93229.846710380.15241.375710390.49242.6734
#Mann= 3 , 0 , 0
 9609.48  0.0725       0 9609.48  0.0725       010390.49  0.0725       0
#XS Ineff= 2 , 0
       0                               0
Bank Sta=9609.48,10390.49
Exp/Cntr=0.3,0.1

Type RM Length L Ch R = 1 ,4256.089,93.352100,93.352100,93.352100
XS GIS Cut Line= 6
1195343.95612878844318.4135808031195473.41030263844221.989807386
1195628.63072617844091.2589187791195675.79844182 844059.14216276
1195795.83099936843963.4692737591195964.72465601843845.495980074
#Sta/Elev= 30
  9609.5185.99289669.722170.51589700.634152.48719759.722121.56729792.834106.1242
9810.02196.120549878.38493.305999895.26390.861889960.59387.926899985.71185.06238
10001.5485.2557510033.3898.1020410041.7799.4457910058.55108.460910079.53116.3401
10086.59120.982510100.51125.591310121.48139.387610149.75145.251410171.83158.0038
10188.48164.232110204.71173.097210229.06182.064310242.46189.154510265.59194.7947
 10287.9205.484910297.39207.080610313.25217.393110333.07226.298210390.51241.6084
#Mann= 3 , 0 , 0
  9609.5  0.0969       0  9609.5  0.0969       010390.51  0.0969       0
#XS Ineff= 2 , 0
       0                               0
Bank Sta=9609.5,10390.51
Exp/Cntr=0.3,0.1

Type RM Length L Ch R = 1 ,4162.737,93.352100,93.352100,93.352100
XS GIS Cut Line= 6
1195373.89998778844372.1620158481195544.12768229844254.210331774
1195673.01924738844174.6306913461195736.38722109844126.034742802
1195888.35745957844029.2223535341196027.03688161843935.350116106
#Sta/Elev= 30
9606.943198.10399677.168172.64919729.058146.22929764.981123.90089838.46190.78472
9894.46885.783349925.07384.553689940.375 85.98079979.68582.7775810004.6384.23184
10029.3688.0666210033.4888.9816610041.7394.05544 10053.695.4504110069.16102.4842
10093.99116.797510119.73123.362710123.62127.794110127.51129.546210139.18 130.188
10154.74140.677710197.53160.227910256.44179.379610263.33187.765410268.33 191.306
 10292.1192.0971   10316205.411810363.41228.670410371.34231.156410393.06234.2143
#Mann= 3 , 0 , 0
9606.943  0.0858       09606.943  0.0858       010393.06  0.0858       0
#XS Ineff= 2 , 0
       0                               0
Bank Sta=9606.943,10393.06
Exp/Cntr=0.3,0.1

Type RM Length L Ch R = 1 ,4069.385,93.352100,93.352100,93.352100
XS GIS Cut Line= 6
1195381.43245651   844438.6501491195602.07356364 844293.88601184
1195674.38074241844257.5941031071195873.01832801844177.733658442
1195980.05280436844114.1172978871196068.63387208844049.167220089
#Sta/Elev= 30
9603.148209.50129627.682198.31729645.035191.9526 9664.09182.63729680.024177.3299
9731.811156.05789749.154150.38589767.505138.72149790.322127.8373 9801.87121.3315
9824.966110.89559871.02193.70399 9888.8885.234719955.14781.04907 9983.3482.33952
9993.68281.7829510073.9583.1292910082.2784.79729 10095.290.7696210109.4899.96197
10130.25106.242610142.25114.205610160.48124.417510179.16129.102910247.63 168.028
10274.76181.295210294.39 192.385 10371.4226.546610387.94234.985410396.87 240.527
#Mann= 3 , 0 , 0
9603.148  0.0825       09603.148  0.0825       010396.87  0.0825       0
#XS Ineff= 2 , 0
       0                               0
Bank Sta=9603.148,10396.87
Exp/Cntr=0.3,0.1

Type RM Length L Ch R = 1 ,3976.033,93.352100,93.352100,93.352100
XS GIS Cut Line= 6
1195422.61915207844516.5990010091195658.12218234844364.291950288
1195728.63604823844331.2806491431195837.18906367844296.274586685
1195938.98933239844244.2073546841196107.84394688844115.206546754
#Sta/Elev= 30
9599.957208.19559623.203198.51469690.066 165.6459711.551156.31189731.361 146.404
9758.809134.67959785.834 124.5389816.719111.05219843.029102.23559876.80287.82614
9906.21679.357819913.54778.1222810021.7376.9217710038.9777.8212210085.0483.44541
10128.5584.8636910132.6887.5503810162.27113.289710166.02114.924410173.51116.0556
10177.26118.325910188.56127.917610193.05129.408610215.95130.7336 10231.6145.3462
10267.62166.263210313.23184.737610352.06206.3214   10365 210.342   10400225.3968
#Mann= 3 , 0 , 0
9599.957  0.0923       09599.957  0.0923       0   10400  0.0923       0
#XS Ineff= 2 , 0
       0                               0
Bank Sta=9599.957,10400
Exp/Cntr=0.3,0.1