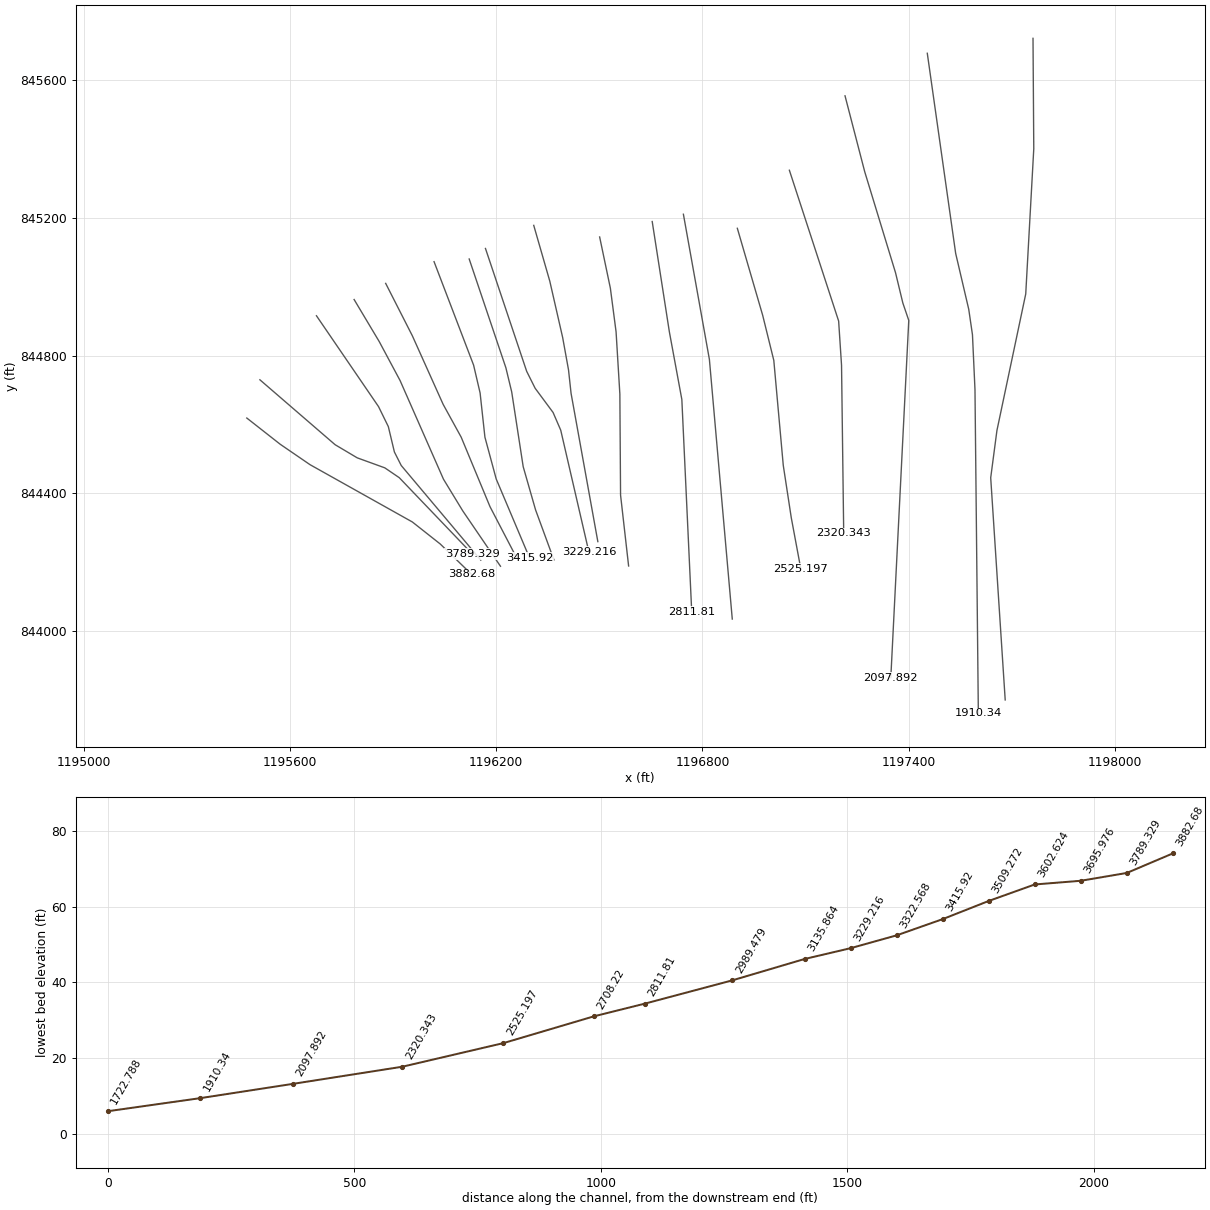
HEC-RAS study 242_ras.prj: 242

--- 242_ras.g01 (geometry) --- (continued)

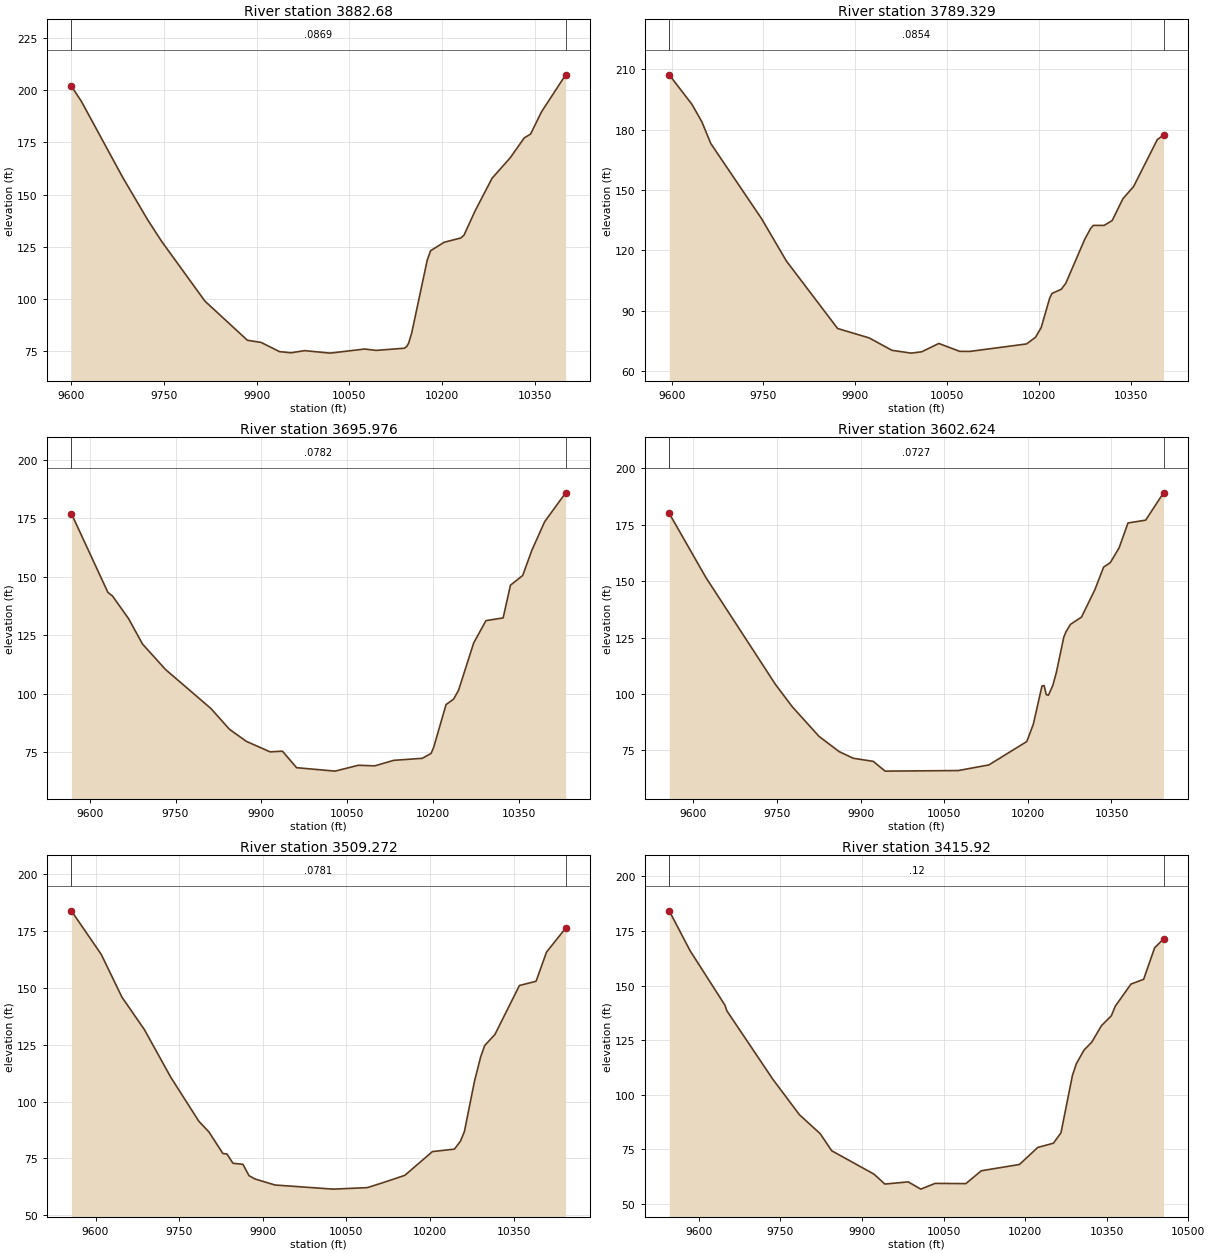
Type RM Length L Ch R = 1 , 3882.68,93.352000,93.352000,93.352000
XS GIS Cut Line= 6
1195474.69644781844619.0385103671195571.88492627844542.809150562
 1195658.6685626844483.433299304 1195956.1363343844316.987657136
1196036.95520597844253.2496311641196128.51487289844164.699800271
#Sta/Elev= 30
 9599.96201.88629616.101194.65259682.815158.32789723.419137.90989746.076127.5647
9816.10398.95793 9884.89 80.19829907.18479.15013 9936.8974.760289955.45674.19722
9977.735 75.232410018.7174.0350210074.5875.9958610093.2175.3438810139.1776.39898
10143.0577.2993110145.9278.8514110150.7983.59527   10176118.600410181.49123.1002
10203.41127.131210230.45129.194210235.55130.557410253.32142.0766   10281157.8051
10310.52167.671610332.96177.097810343.31  178.9510360.88189.558310400.03 207.324
#Mann= 3 , 0 , 0
 9599.96  0.0869       0 9599.96  0.0869       010400.03  0.0869       0
#XS Ineff= 2 , 0
       0                               0
Bank Sta=9599.96,10400.03
Exp/Cntr=0.3,0.1

Type RM Length L Ch R = 1 ,3789.329,93.352100,93.352100,93.352100
XS GIS Cut Line= 6
1195512.81002744844730.1464951481195731.55595979844541.511100378
 1195795.8861656844503.3305485771195876.08945585844474.266874689
 1195918.1617089 844445.644994891196130.53094874844223.912669969
#Sta/Elev= 30
9596.177207.3057 9633.22192.64899649.499183.92639663.924173.19939746.982135.7689
9787.612114.68999871.27181.127329922.73676.455239960.13570.268439991.58668.87537
10008.7369.54733 10036.773.6807810070.7369.76317 10087.669.7355510179.9773.44605
10194.5576.7296410203.8681.5505110217.8296.23888 10221.698.5805310236.77100.6384
10244.19103.676810275.19125.567910284.62130.854410289.12132.412910306.91132.4188
10319.99134.847910337.44145.6742 10354.9151.735710393.71175.124110403.81 177.315
#Mann= 3 , 0 , 0
9596.177  0.0854       09596.177  0.0854       010403.81  0.0854       0
#XS Ineff= 2 , 0
       0                               0
Bank Sta=9596.177,10403.81
Exp/Cntr=0.3,0.1

Type RM Length L Ch R = 1 ,3695.976,93.352100,93.352100,93.352100
XS GIS Cut Line= 6
1195677.26314089844916.2574813621195857.87541022844652.171705702
1195886.33461691844594.0897395041195903.94696248 844520.35845379
1195923.82138938844481.1134123671196155.17173325844206.259301505
#Sta/Elev= 30
9567.885176.97149631.719 143.264 9639.79141.71959668.042131.96199692.258121.1657
9732.617110.24379812.02493.562949844.20884.72458 9873.8579.545959915.19375.07211
9936.93875.335479961.70968.2800310028.9666.8126610069.65 69.318910098.3269.07248
10131.5871.4261710181.5272.2975310196.92 74.410710201.4777.0878210223.0595.29284
10236.1297.5856510244.83101.372410271.29121.618610292.75131.1865 10322.8132.3406
10335.62146.336510356.97150.467810372.97161.224610395.41173.4936 10432.1185.8365
#Mann= 3 , 0 , 0
9567.885  0.0782       09567.885  0.0782       0 10432.1  0.0782       0
#XS Ineff= 2 , 0
       0                               0
Bank Sta=9567.885,10432.1
Exp/Cntr=0.3,0.1

Type RM Length L Ch R = 1 ,3602.624,93.352100,93.352100,93.352100
XS GIS Cut Line= 6
1195786.80546598844963.4380229371195859.75943697844841.360651792
1195920.47716217844727.996109641 1196046.7133211844441.250287417
1196102.85629253844349.0824902051196212.47238107844188.340019763
#Sta/Elev= 30
9556.628180.03339622.356151.63419747.181104.25719776.95594.470669825.33881.24304
9861.51974.477869886.80171.54396 9922.6570.159919943.87465.8367210075.2166.09424
10130.0468.5798110198.1278.9618610209.7786.60168 10225.3 103.54610229.18 103.763
10233.0699.7287610236.94 99.483610244.71103.773110251.19109.622110264.47125.2074
10268.44127.595510276.38130.852310296.24134.091710320.06146.139310335.95156.2454
10347.86 158.20210363.75164.801210379.63175.7935 10411.4177.050910443.38189.1492
#Mann= 3 , 0 , 0
9556.628  0.0727       09556.628  0.0727       010443.38  0.0727       0
#XS Ineff= 2 , 0
       0                               0
Bank Sta=9556.628,10443.38
Exp/Cntr=0.3,0.1

Type RM Length L Ch R = 1 ,3509.272,93.352100,93.352100,93.352100
XS GIS Cut Line= 6
1195878.61108717845010.3368123681195956.17270384844858.007347719
1196045.72933514844658.7673259911196098.21811715844563.354910274
1196182.02753301844361.4066984751196260.43979491844210.861787627
#Sta/Elev= 30
9556.618183.87449610.283164.68469647.315145.91499687.583131.64979734.987110.6718
9785.34591.31849 9803.3386.658019828.509 77.13779835.70376.955779846.49472.85886
 9864.4872.395599875.27167.412769886.06265.947069922.03263.2935210026.3261.48508
10087.6462.1454210115.9464.3475910154.8567.5490210204.3777.9974510243.8179.07186
10254.5782.5342810261.7486.8067710279.81108.909510290.81119.571410298.14124.6421
10316.48129.504410360.48151.043810390.32152.894610409.01 165.70210443.36176.2577
#Mann= 3 , 0 , 0
9556.618  0.0781       09556.618  0.0781       010443.36  0.0781       0
#XS Ineff= 2 , 0
       0                               0
Bank Sta=9556.618,10443.36
Exp/Cntr=0.3,0.1

Type RM Length L Ch R = 1 , 3415.92,93.352100,93.352100,93.352100
XS GIS Cut Line= 6
1196019.32031678845073.4197735121196134.31858958844772.735905325
 1196153.2062715844691.8538345781196167.22666492844563.420960546
1196200.02349647844441.9765446911196296.82604986 844213.04005954
#Sta/Elev= 30
9545.415184.23789583.715 165.9639647.858141.00519651.394138.40969735.979107.0308
9784.914 90.78029822.97582.120169844.17974.286449921.951 63.57329942.00759.01627
9985.03460.0126410008.0456.6914210034.4959.3237210090.9959.2198910119.4165.10608
10189.5567.9901510223.2375.8016610251.9977.7325810265.9382.4850310287.06108.8703
10294.15114.120310308.32120.4367 10322.5124.020110340.42131.603110358.52136.1122
10365.76140.505510394.72150.671810417.99152.852610438.17 167.28710454.55171.3419
#Mann= 3 , 0 , 0
9545.415    0.12       09545.415    0.12       010454.55    0.12       0
#XS Ineff= 2 , 0
       0                               0
Bank Sta=9545.415,10454.55
Exp/Cntr=0.3,0.1

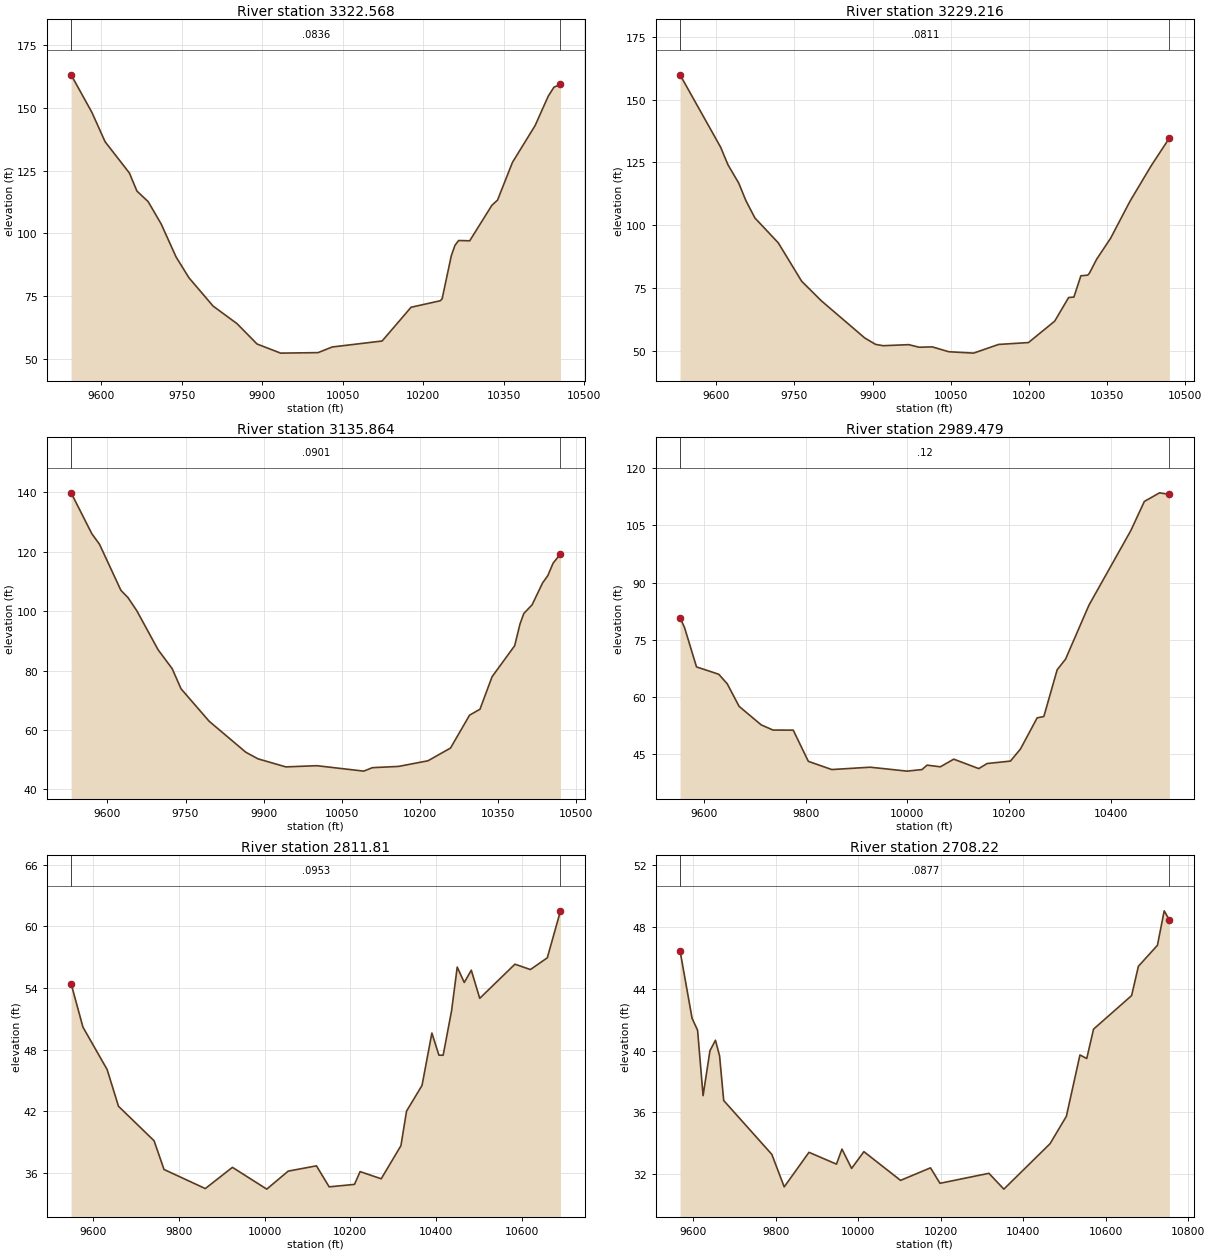
Type RM Length L Ch R = 1 ,3322.568,93.352100,93.352100,93.352100
XS GIS Cut Line= 6
1196121.47213274845081.2442728261196228.12885781844765.312370753
1196245.08469436844695.0951976431196278.54329176844477.640501738
1196314.53466506844352.1061635341196367.92852762844206.679090655
#Sta/Elev= 30
9544.203 163.1059582.971148.1388 9607.41136.51919652.796124.04199666.761116.8716
9687.708 112.6729712.065103.73569739.66890.674339763.82182.349049808.61871.13957
9853.12764.151169890.60456.03057 9934.4852.4118810004.1952.6116310030.59 54.8571
10123.5757.2327410177.4770.6606310231.8473.2447410235.2773.9758510252.4191.15184
10259.2695.3002510266.1297.2040110286.6997.0868610328.13111.255510338.52113.2655
10366.29128.269610408.48142.899410433.09 154.65910443.64 158.18810455.82159.3116
#Mann= 3 , 0 , 0
9544.203  0.0836       09544.203  0.0836       010455.82  0.0836       0
#XS Ineff= 2 , 0
       0                               0
Bank Sta=9544.203,10455.82
Exp/Cntr=0.3,0.1

Type RM Length L Ch R = 1 ,3229.216,93.352100,93.352100,93.352100
XS GIS Cut Line= 6
1196168.81933314845111.7961260211196288.60667837844754.954506328
1196313.22273234 844705.660040851196365.47488091844635.153324426
1196387.70100655844583.7657427141196469.56834342844229.892283967
#Sta/Elev= 30
9530.579 159.8549608.578130.99069622.496124.03879643.257116.69359657.038109.7046
9674.265 102.8329719.05492.936179763.84377.666479801.74269.843649884.89355.06596
 9905.8252.498889920.14651.981929969.178 52.39849989.48451.3692710014.5851.50634
 10046.249.5767910093.72 49.024310141.6752.4841610199.0353.2310910249.2961.75131
 10276.171.1830310286.1571.3390110299.5579.8135410312.9580.09652 10316.380.99084
10329.7186.3913610356.5194.7473410393.66109.463710434.26123.587310469.41134.7028
#Mann= 3 , 0 , 0
9530.579  0.0811       09530.579  0.0811       010469.41  0.0811       0
#XS Ineff= 2 , 0
       0                               0
Bank Sta=9530.579,10469.41
Exp/Cntr=0.3,0.1

Type RM Length L Ch R = 1 ,3135.864,146.384400,146.384400,146.384400
XS GIS Cut Line= 6
1196309.21050487845178.9382945081196355.92226455845016.688356352
1196393.31793658844853.0699274241196410.37099033844758.861810503
1196417.76527455 844690.845209461196495.63618602844259.878753172
#Sta/Elev= 30
9530.549139.8622 9570.14126.13159585.009 122.5439626.019107.05059639.627104.5903
9656.636100.14619697.45887.019359724.47580.651029741.35273.904979795.32462.97187
9865.77152.520289889.11950.303769942.46547.5980210002.06 47.998610091.9346.16998
10108.6347.3372110158.73 47.758210215.2249.6553310258.4253.9376210294.9865.00995
10314.9266.9980210338.1877.9527410381.5388.3951210391.5895.6048510399.0899.24577
10415.02102.178510435.12109.548710445.16112.000210455.21116.167110469.44119.3075
#Mann= 3 , 0 , 0
9530.549  0.0901       09530.549  0.0901       010469.44  0.0901       0
#XS Ineff= 2 , 0
       0                               0
Bank Sta=9530.549,10469.44
Exp/Cntr=0.3,0.1

Type RM Length L Ch R = 1 ,2989.479,177.669400,177.669400,177.669400
XS GIS Cut Line= 6
1196500.87342402845145.2555751641196532.08122188844996.302158756
1196548.68391757 844869.373655211196559.67930689844688.677973913
1196561.72483758844395.1759559261196585.13438809844189.072382548
#Sta/Elev= 30
9553.11880.794919561.92678.207569585.50367.880329629.17665.961779645.88763.46417
9669.28257.530959712.67352.676999735.88951.317859775.68851.294489805.39743.10964
9851.52740.954989927.12541.571389999.437 40.541510028.9940.9555410038.8442.11099
10065.0841.6773410091.3343.6812110140.5441.2067910156.9542.5348610202.8843.17799
10222.5646.3477410255.3854.5166110268.5154.8671610294.7767.1355910311.1969.91297
10357.25 84.080510439.73103.683210466.19111.292210496.09 113.55310515.48113.1565
#Mann= 3 , 0 , 0
9553.118    0.12       09553.118    0.12       010515.48    0.12       0
#XS Ineff= 2 , 0
       0                               0
Bank Sta=9553.118,10515.48
Exp/Cntr=0.3,0.1

Type RM Length L Ch R = 1 , 2811.81,103.590100,103.590100,103.590100
XS GIS Cut Line= 4
1196653.74868903845190.1357270631196703.64845872844869.567509592
1196739.93920034844672.992659241 1196768.6693708844056.050052032
#Sta/Elev= 30
9548.69254.411799576.23350.186039632.67946.050389659.24242.46389 9742.2539.10333
9765.49336.300659861.78334.441449925.11836.5106110005.1934.3861110055.2336.14173
 10121.236.6566710150.7634.6086910209.8834.8476310223.0136.0945510272.2835.39502
10318.2638.62021 10331.441.9949310367.5344.4999210390.5249.6049310406.9447.44924
10416.7947.44019 10436.551.7863810449.6456.0399310466.0654.5331510482.4855.73357
10502.1952.99074 10584.356.3189810620.4255.7962610659.8456.9401910690.6361.52243
#Mann= 3 , 0 , 0
9548.692  0.0953       09548.692  0.0953       010690.63  0.0953       0
#XS Ineff= 2 , 0
       0                10225.59       0
Bank Sta=9548.692,10690.63
Exp/Cntr=0.3,0.1

Type RM Length L Ch R = 1 , 2708.22,183.023300,183.023300,183.023300
XS GIS Cut Line= 3
1196744.47554302845211.3053263281196820.08125469844789.425455213
1196886.61428097844034.880452752
#Sta/Elev= 30
9568.34246.460649597.49742.091929610.82941.317019624.16237.080829640.827 39.9916
 9654.1640.668759664.15939.653039674.15836.765149790.81733.276169820.81531.17026
9880.81133.410629947.47332.645469960.80533.619419984.13732.3681210013.9333.45324
10102.8631.5930210175.32 32.405410198.37 31.404410316.9432.0514910353.1731.02666
10465.1533.9686410504.6735.7436310537.6139.7149110554.0739.4846210570.5441.38783
10662.7643.5589910679.2345.4582710725.34 46.816310741.8149.0491910754.4248.44685
#Mann= 3 , 0 , 0
9568.342  0.0877       09568.342  0.0877       010754.42  0.0877       0
#XS Ineff= 2 , 0
       0                10196.79       0
Bank Sta=9568.342,10754.42
Exp/Cntr=0.3,0.1

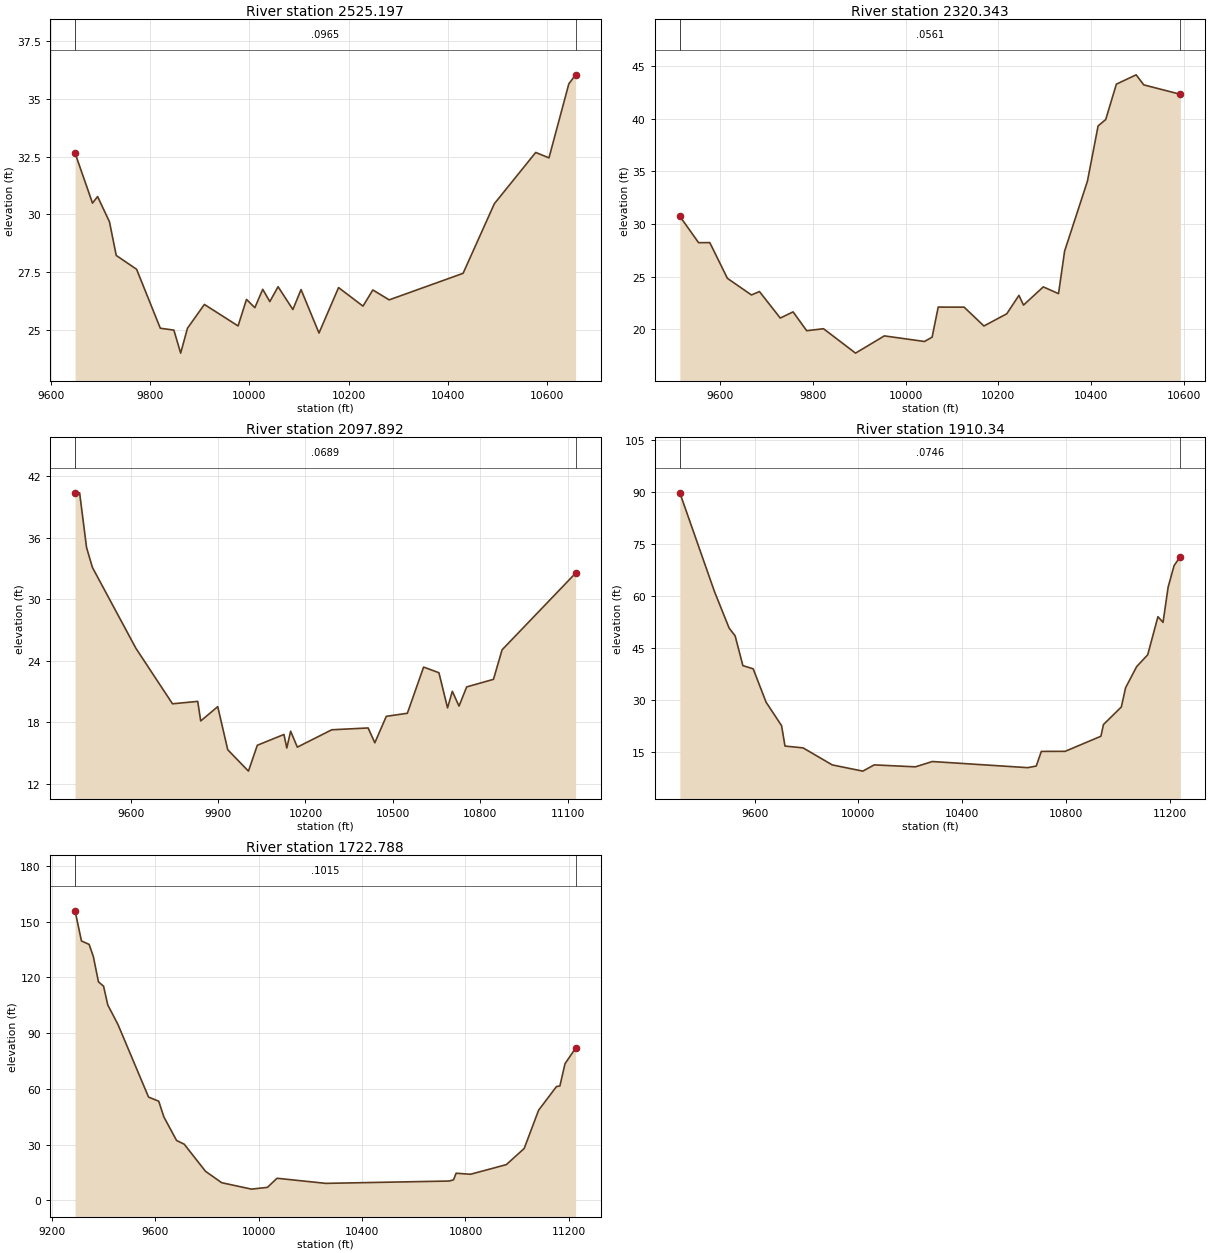
Type RM Length L Ch R = 1 ,2525.197,204.853400,204.853400,204.853400
XS GIS Cut Line= 6
1196901.34344649845170.4332838411196975.07800857844917.494612444
1197007.41035451844786.5231796231197034.92883618844481.496767815
1197058.18363992844329.4665228221197085.75171525844181.644714529
#Sta/Elev= 30
9648.77632.657739683.93930.486779694.19130.771829718.11329.676759731.782 28.2158
9772.79127.616459820.63525.057889847.97424.975839861.64323.977459875.31325.05652
9909.48726.089719977.36825.157129994.33326.3084410011.1625.9489410027.0826.74591
10041.3826.2134510058.0226.8597310087.8225.8703610104.3326.7345910140.4824.84952
10179.9326.8210110229.2226.0162710248.9826.7184110281.9826.2886710430.9327.43987
10493.99 30.460610577.3532.6845510604.0532.44891 10644.135.6607110657.7636.05256
#Mann= 3 , 0 , 0
9648.776  0.0965       09648.776  0.0965       010657.76  0.0965       0
#XS Ineff= 2 , 0
       0                10132.95       0
Bank Sta=9648.776,10657.76
Exp/Cntr=0.3,0.1

Type RM Length L Ch R = 1 ,2320.343,222.450700,222.450700,222.450700
XS GIS Cut Line= 4
1197052.68966469845339.1165630071197195.96747878844900.855013952
1197204.39558551844772.3263866011197210.71666557844283.496197268
#Sta/Elev= 30
9513.53130.74033 9553.9328.232859578.09228.239929616.061 24.84689667.83723.27126
9685.09523.593449729.96721.078579757.58121.664029786.96619.874819823.16320.06569
9892.19817.749139954.32819.3859710040.7818.8539310057.2219.2666910070.3722.11951
10126.21 22.113610168.8720.3254710218.0921.4828610244.3323.2305810254.1822.30833
10296.8324.0369310329.6423.3932710342.7727.4325210391.9834.0727410414.9539.31539
10431.3639.9239210454.3243.2797310496.9844.1659510513.3843.2113810592.2942.31821
#Mann= 3 , 0 , 0
9513.531  0.0561       09513.531  0.0561       010592.29  0.0561       0
#XS Ineff= 2 , 0
       0                10103.42       0
Bank Sta=9513.531,10592.29
Exp/Cntr=0.3,0.1

Type RM Length L Ch R = 1 ,2097.892,187.552400,187.552400,187.552400
XS GIS Cut Line= 6
1197214.54204325845555.3779030841197271.84161656845334.712236932
1197361.42645193845041.2885519091197382.69881335844953.296283411
1197399.93534236844902.784069992 1197347.6733996843864.197888315
#Sta/Elev= 30
9409.14840.31471 9424.8140.373979448.53735.043859468.74133.092099618.01925.20251
9743.66919.785389830.24820.02025 9840.5618.110179898.99719.506459933.37115.30068
10004.4613.2138610034.8415.7374310126.31 16.790510136.1615.46889 10149.317.10907
 10172.315.5554810290.5617.2492710415.3917.4268310438.3815.97946 10477.818.56328
10550.0718.8606410605.9223.3686610658.4822.8171510688.0419.3870910704.4621.00663
10727.4619.5621410753.74  21.43410845.7222.1714110875.2825.0519111127.74 32.5367
#Mann= 3 , 0 , 0
9409.148  0.0689       09409.148  0.0689       011127.74  0.0689       0
#XS Ineff= 2 , 0
       0                10201.96       0
Bank Sta=9409.148,11127.74
Exp/Cntr=0.3,0.1

Type RM Length L Ch R = 1 , 1910.34,187.552300,187.552300,187.552300
XS GIS Cut Line= 6
1197453.78420585845679.1090836971197536.33182243845097.473098889
1197574.37766975844934.9242900461197585.17324638844861.099907249
1197592.50092614844701.3209903991197602.26982996843760.740101144
#Sta/Elev= 30
9311.767 89.69599445.422 61.19639501.75550.712659524.95148.444729554.77439.87285
9594.53938.948189644.24429.327039703.89122.568919717.14616.681729786.73416.16126
9899.40111.24425 10017.29.45345810061.1911.2528810219.79 10.692510285.43 12.2224
10652.91 10.453910685.7210.91811 10705.415.1365210797.2715.1633410935.0819.51157
10944.9222.8826311013.8227.9555811030.2233.4992611072.8839.5918711115.5343.00287
 11154.953.9780511174.5952.3458611194.2862.5134911217.2468.7231711241.4871.33296
#Mann= 3 , 0 , 0
9311.767  0.0746       09311.767  0.0746       011241.48  0.0746       0
#XS Ineff= 2 , 0
       0                10308.05       0
Bank Sta=9311.767,11241.48
Exp/Cntr=0.3,0.1

Type RM Length L Ch R = 1 ,1722.788,187.552400,187.552400,187.552400
XS GIS Cut Line= 6
1197761.26538953845722.4881158171197763.47416586845401.213098422
1197740.09045392844979.5482659941197656.33225667844582.879922226
1197638.22506833844445.4447680711197680.39482996843799.802601144
#Sta/Elev= 30
9290.812155.84889315.609139.61179345.145 137.7829361.553131.19229381.244117.6217
9400.935115.28039417.344105.15669456.72594.622139574.842 55.56039614.21653.34411
9633.91844.932459683.17532.197049712.72930.19358 9794.8915.619349857.3679.471913
9972.4165.99997710034.496.94723110071.4211.8538210259.74 9.10233 10737.510.35921
10753.9411.0432610763.8114.56467 10819.714.0087910957.7919.1917511026.8327.85865
11082.7248.5041711151.7761.2349311164.9261.5381311184.6573.4998611225.6881.91766
#Mann= 3 , 0 , 0
9290.812  0.1015       09290.812  0.1015       011225.68  0.1015       0
#XS Ineff= 2 , 0
       0                10374.08       0
Bank Sta=9290.812,11225.68
Exp/Cntr=0.3,0.1