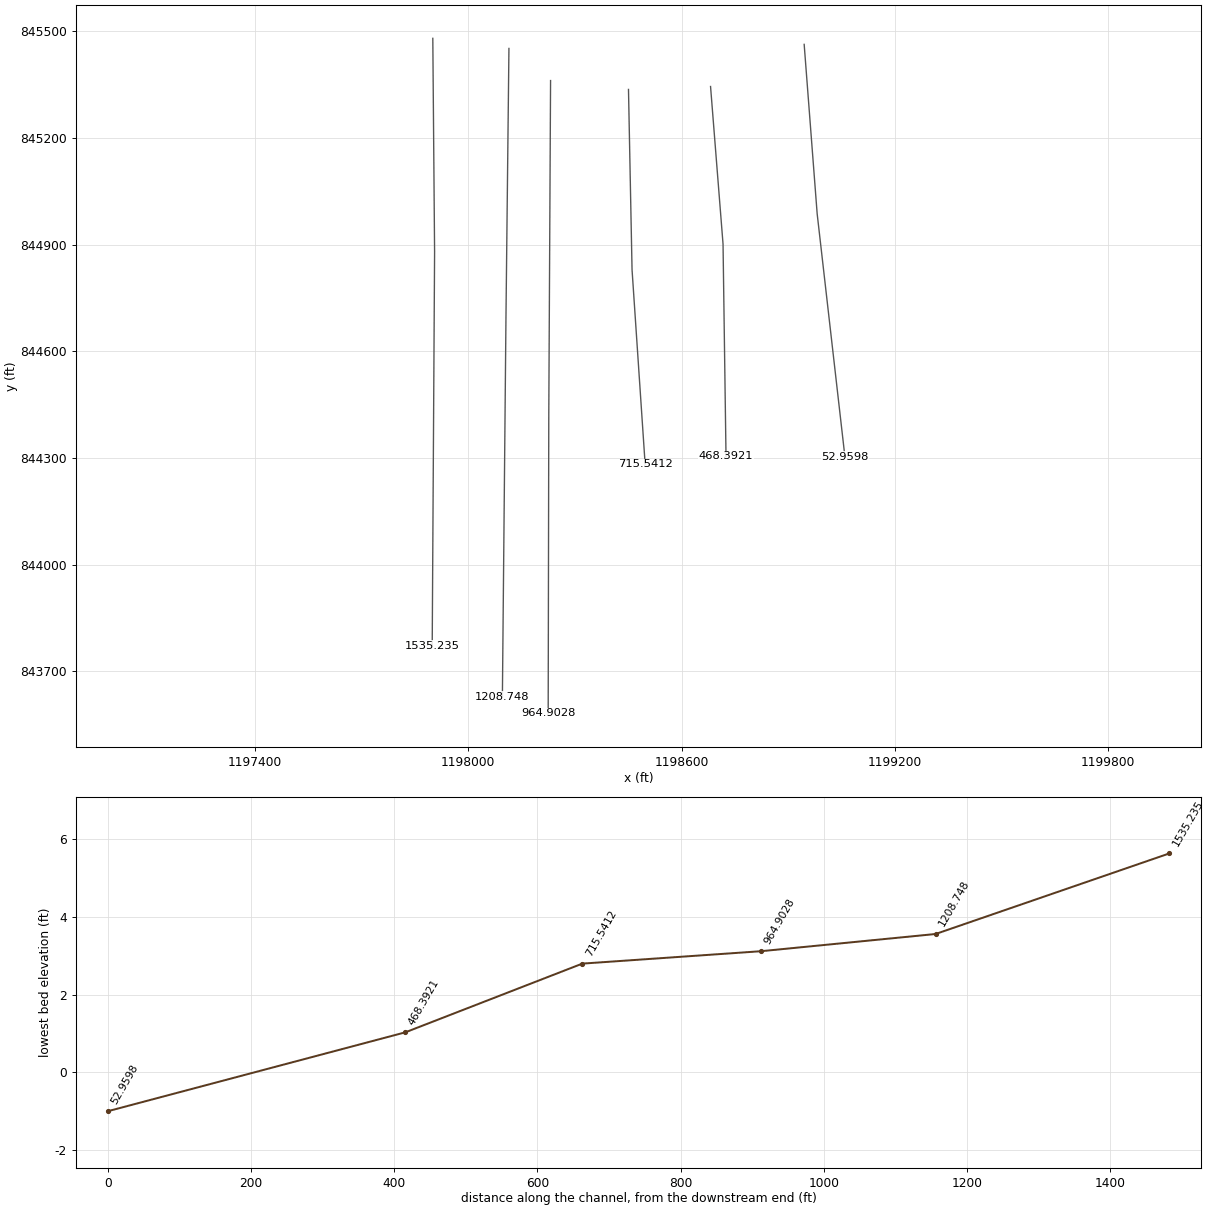
HEC-RAS study 242_ras.prj: 242

--- 242_ras.g01 (geometry) --- (continued)

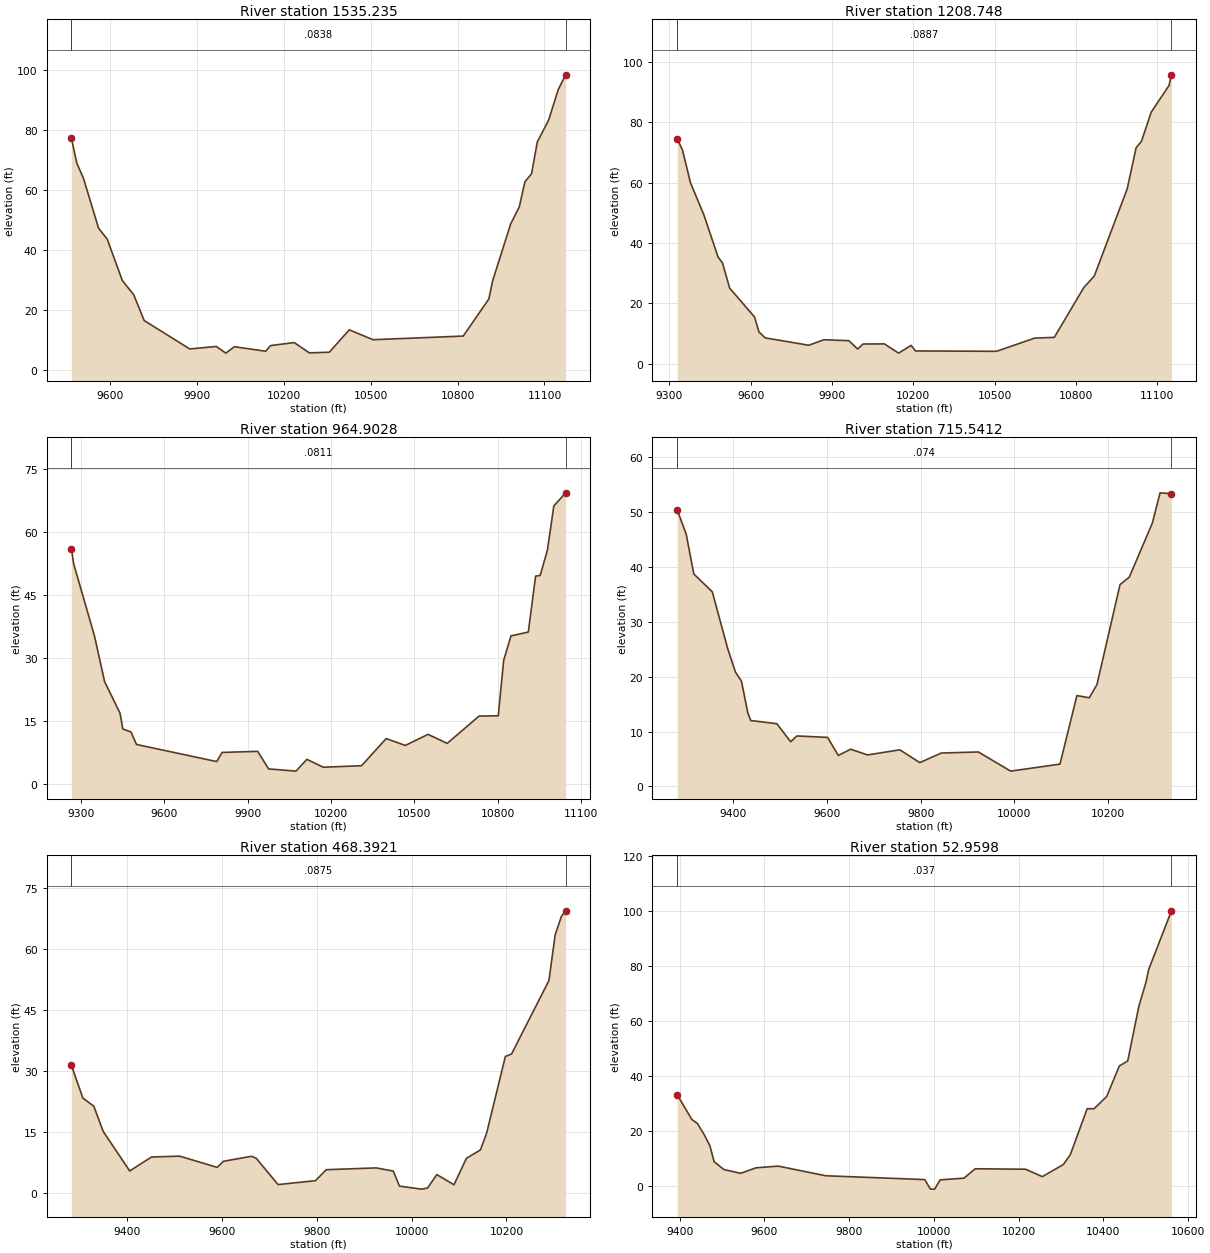
Type RM Length L Ch R = 1 ,1535.235,326.487800,326.487800,326.487800
XS GIS Cut Line= 3
1197900.56240302845480.0275100021197905.58020505844879.563860372
1197898.88980228843772.302200004
#Sta/Elev= 30
9465.34377.350119483.89369.00371 9506.8664.001599559.35547.269099588.88343.69961
9641.379 29.8401 9680.7525.09802 9716.8416.510219874.3267.0314949966.1927.865101
9999.0025.64071910028.537.776279 10136.86.267367 10153.28.15423210235.239.157876
10287.725.71888710356.625.95000210425.5213.4065610507.5410.1150610819.2311.32816
10907.8123.6949310920.9329.7968510983.2748.72999 11012.854.3643811032.4862.77351
11055.4565.4582811075.14 76.030711114.5183.3596811147.3293.4635911173.1198.41227
#Mann= 3 , 0 , 0
9465.343  0.0838       09465.343  0.0838       011173.11  0.0838       0
#XS Ineff= 2 , 0
       0                10458.67       0
Bank Sta=9465.343,11173.11
Exp/Cntr=0.3,0.1

Type RM Length L Ch R = 1 ,1208.748,243.844800,243.844800,243.844800
XS GIS Cut Line= 3
1198114.65529197845451.5932981671198106.29228854844693.905183181
1198096.25668436843628.458540216
#Sta/Elev= 30
9329.08774.492099348.73170.76271 9378.2659.902569427.47549.335579479.97235.35541
9496.37733.393489522.62525.093069614.49415.514129630.89910.555719653.8678.607331
9814.6376.1710019870.4157.9916919962.2847.6806899995.0944.91652810014.786.577609
10093.53 6.6178910146.023.56500610191.956.13226210208.364.28549310506.934.163714
10648.018.54016810720.19 8.7718210828.46 25.171910867.8429.0963610989.2357.94051
11022.04 71.503211041.7373.6386511077.8283.3095511143.4492.1166211152.3295.63648
#Mann= 3 , 0 , 0
9329.087  0.0887       09329.087  0.0887       011152.32  0.0887       0
#XS Ineff= 2 , 0
       0                 10296.9       0
Bank Sta=9329.087,11152.32
Exp/Cntr=0.3,0.1

Type RM Length L Ch R = 1 ,964.9028,249.361600,249.361600,249.361600
XS GIS Cut Line= 3
1198231.73734066845361.2728606161198226.71953857844419.598669127
1198225.04693791843581.625720739
#Sta/Elev= 30
9264.90556.097369272.96752.530069348.42835.206749384.51724.428629440.29216.88739
9450.13513.148589479.66312.436689499.348 9.469579788.0665.3980369807.7517.571249
9935.7057.8306859975.0763.648614 10073.53.12175910112.875.92856710171.934.046597
10309.724.41396210398.3110.87288 10467.29.23915310549.2311.8740710618.129.723861
10732.9516.2278610801.8516.2965610821.5429.5381810847.7835.3200910910.12 36.2247
10936.3649.5462710952.7749.6964410979.0255.7730311001.9866.2582911044.5769.36827
#Mann= 3 , 0 , 0
9264.905  0.0811       09264.905  0.0811       011044.57  0.0811       0
#XS Ineff= 2 , 0
       0                10144.12       0
Bank Sta=9264.905,11044.57
Exp/Cntr=0.3,0.1

Type RM Length L Ch R = 1 ,715.5412,247.149100,247.149100,247.149100
XS GIS Cut Line= 3
 1198450.8826429845336.3079126121198460.88363591844829.385839492
1198497.68085125844282.445412099
#Sta/Elev= 30
9279.97950.457979299.16946.048199315.57638.743099354.95435.497839387.76925.16523
9404.17620.907289417.30219.188379430.42813.556049436.99112.030049492.77611.45079
9522.309 8.156299535.4359.2169169601.0648.9561559624.035  5.65579650.2866.802238
9686.3835.7536399755.2936.6863139797.9754.3611679844.0116.1039439922.9296.295067
9991.9822.80247510097.214.07986610133.3816.5823610159.6816.1718710176.12 18.5605
10225.4536.8213310245.18 38.1693 10294.548.0533510310.94 53.548210335.18 53.3825
#Mann= 3 , 0 , 0
9279.979   0.074       09279.979   0.074       010335.18   0.074       0
#XS Ineff= 2 , 0
       09466.218                       0
Bank Sta=9279.979,10335.18
Exp/Cntr=0.3,0.1

Type RM Length L Ch R = 1 ,468.3921,415.432300,415.432300,415.432300
XS GIS Cut Line= 3
1198681.66692774845344.5468536621198716.79154234844901.307669387
1198725.15454583844304.189221144
#Sta/Elev= 30
9282.95731.443999307.17723.384699330.21521.395439349.96215.213599405.911 5.49329
9451.9868.9246919511.2269.1242059590.2136.3780949603.378 7.859379662.6189.100196
9672.4918.6178429718.5672.1522629797.3423.102943 9820.315.8092529925.3076.242887
  9961.45.4681829974.5241.77889610020.461.03288110033.591.29831710053.274.602157
10089.362.10393310115.618.59949910145.1410.6604210158.27 14.796910197.6433.58637
10210.7734.2075910289.5252.2344310302.6463.4428210315.7667.9812910324.7669.34874
#Mann= 3 , 0 , 0
9282.957  0.0875       09282.957  0.0875       010324.76  0.0875       0
#XS Ineff= 2 , 0
       09462.753                       0
Bank Sta=9282.957,10324.76
Exp/Cntr=0.3,0.1

Type RM Length L Ch R = 1 , 52.9598,0.000000,0.000000,0.000000
XS GIS Cut Line= 3
 1198944.9337295845463.0870997761198981.48467371844986.725776181
1199059.62863806844302.530143693
#Sta/Elev= 30
9394.05733.285529428.57524.311369441.737 22.8345 9458.1918.679359471.35114.70655
9481.223 8.985869504.256 6.113579543.7424.7359029579.937 6.732819632.5857.351262
9744.4613.8560149978.4622.4589679991.671  -0.99910001.58  -0.99910014.792.367537
10070.92    2.9810097.346.38642910216.226.22229910255.843.53511510305.38 7.93733
10321.8911.5398310361.5128.1647910378.0228.1920510407.7432.6429510437.4643.68117
10457.2845.5135910483.6965.44108 10500.2 73.966610506.8178.7148810560.4699.98888
#Mann= 3 , 0 , 0
9394.057   0.037       09394.057   0.037       010560.46   0.037       0
#XS Ineff= 2 , 0
       09616.669                       0
Bank Sta=9394.057,10560.46
Exp/Cntr=0.3,0.1